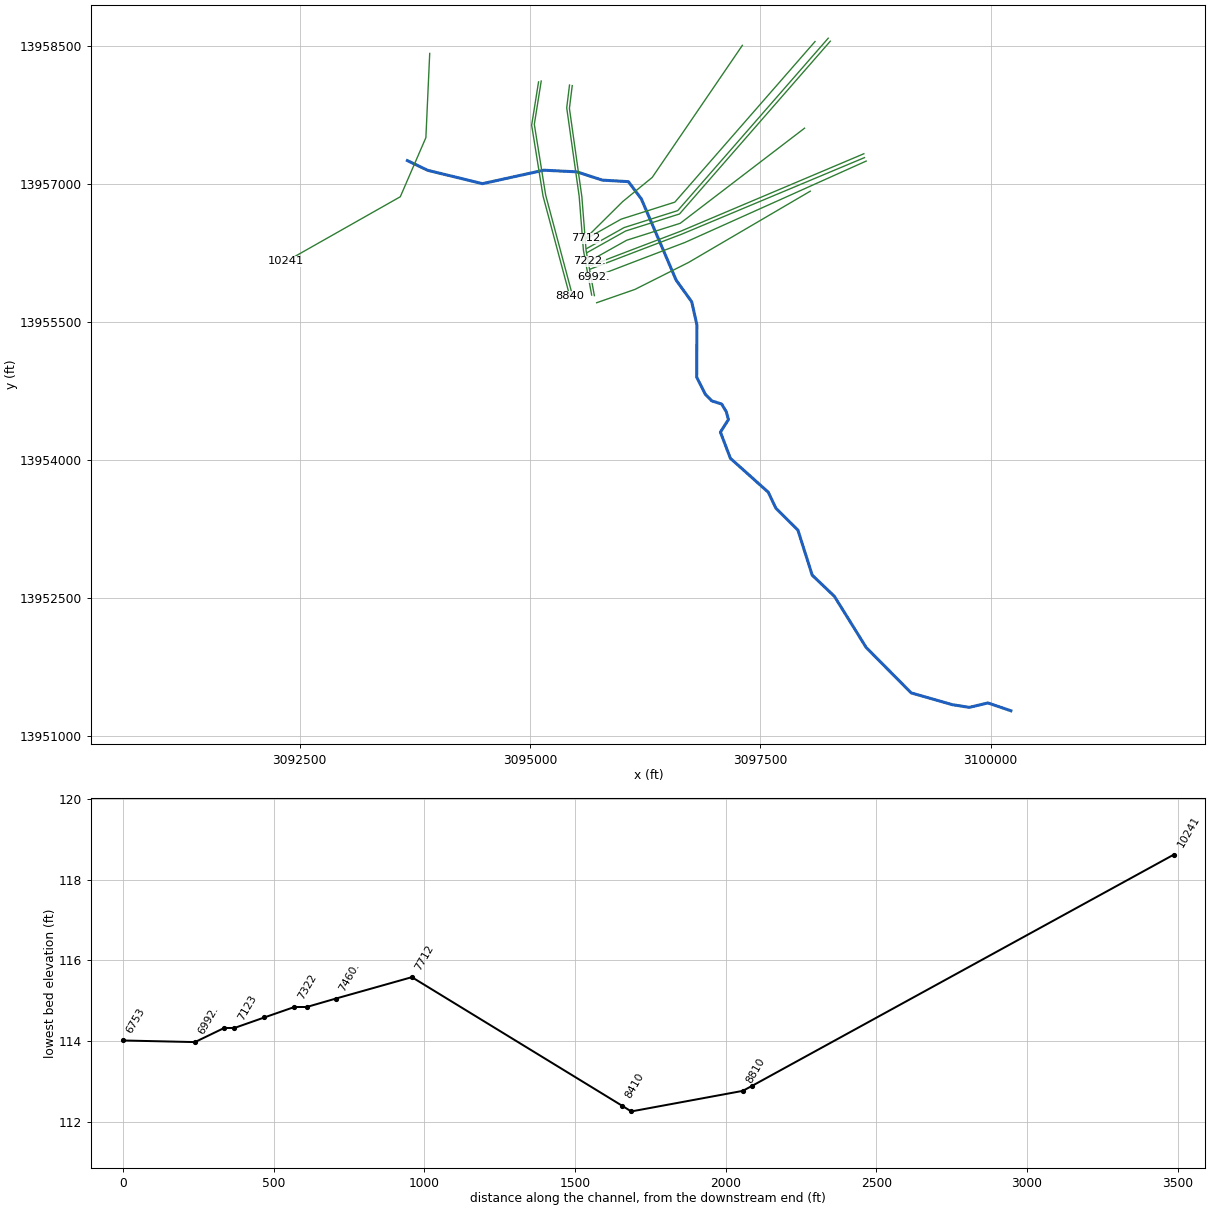
--- K120-03-00.prj (project) ---

Proj Title=K120-03-00
Current Plan=p02
Default Exp/Contr=.3,.1
English Units
Geom File=g01
Flow File=f01
Flow File=f02
Plan File=p01
Plan File=p02
Y Axis Title=Elevation
X Axis Title(PF)=Main Channel Distance
X Axis Title(XS)=Station
BEGIN DESCRIPTION:
HCFCD MODEL SUMMARY METADATA
The purpose of this summary is to document the high points of hydrologic and hydraulic models filed within the HCFCD Model and Map Management (M3) system.  The document includes references to the project that prompted the creation or update of the model.
DESCRIPTION OF PROJECT:
The following model was the hydraulic model which represented the effective condition of Harris County's watersheds.
PURPOSE OF PROJECT:
Development of effective models to support the National Flood Insurance Program.
HCFCD Watershed Unit ID: K
M3 Study Identifier: 2007_Effective_K
Engineer: HCFCD
Project Name: EffectiveFEMA Study for watershed Cypress Creek (K)
Study Completion Date: 6/18/2007
FEMA Case Number: [No Data]
FEMA Approval Date: [No Date in Database]
Vertical Datum: NAVD 1988
Datum Note: 2001 ADJ
HYDRAULICS
HCFCD Unit No.:  K120-03-00
Hydraulic Program Name: HEC-RAS
Hydraulic Program Version: 3.0.1
Steady Hydraulic Model: Yes
Unsteady Hydraulic Model: No
Update1:
The effective FEMA hydraulic model for unit number K120-03-00 has been updated by FEMA LOMR 16-06-1373P with an effective date of 08/09/2016.
END DESCRIPTION:
DSS Export Rating Curves= 0
DSS Export Rating Curve Sorted= 0
DSS Export Volume Flow Curves= 0
DXF Filename=K120-03-00.
DXF OffsetX= 0
DXF OffsetY= 0
DXF ScaleX= 1
DXF ScaleY= 10

--- K120-03-00.p02 (plan) ---

Plan Title=Effective FW 2016
Version=Version 3.0.1  May 2012
Short Identifier=Eff+LOMR FW
Geom File=g01
Flow File=f02
Subcritical Flow
K Sum by GR= 0
Std Step Tol= 0.01
Critical Tol= 0.01
Num of Std Step Trials= 20
Max Error Tol= 0.3
Flow Tol Ratio= 0.001
Split Flow NTrial= 30
Split Flow Tol= 0.02
Split Flow Ratio= 0.02
Log Output Level= 0
Friction Slope Method= 1
Unsteady Friction Slope Method= 2
Parabolic Critical Depth
Global Vel Dist= 0 , 0 , 0
Global Log Level= 0
CheckData=True
Encroach Param=-1 ,0,0, 2
Encroach River=K120-03-00
Encroach Reach=K120-03-00_0006
Encroach Node=10241
       1 4955.45 5055.45
Encroach Node=8840
       1    4955    5058
Encroach Node=8810
       1  4969.1    5028
Encroach Node=8625
       1  4969.1    5028
Encroach Node=8440
       1  4969.1    5028
Encroach Node=8410
       1    4955    5058
Encroach Node=7712
       1  4864.7  5139.7
Encroach Node=7460.
       1    4870    5143
Encroach Node=7363
       1 4732.41  5051.9
Encroach Node=7342.5
       1 4732.41  5051.9
Encroach Node=7322
       1 4732.41  5051.9
Encroach Node=7222.
       1 4680.66  5051.9
Encroach Node=7123
       1    4852    5152
Encroach Node=7106
       1    4852    5152
Encroach Node=7089
       1    4852    5152
Encroach Node=6992.
       1    4881    5141
Encroach Node=6753
       1 4909.62 5107.68
Encroach Node=6713.5
       1 4909.62 5107.68
Encroach Node=6674
       1 4909.62 5107.68
Encroach Node=6378.
       1  4950.1    5139
Encroach Node=6064.
       1    4903    5071
Encroach Node=5957
       1    4875    5058
Encroach Node=5936.5
       1    4875    5058
Encroach Node=5916
       1    4875    5058
Encroach Node=5790
       1  4917.5  5047.5
Encroach Node=5504.
       1  4961.7  5021.7
Encroach Node=5315
       1  4944.7 5075.67
Encroach Node=5294.5
       1  4944.7 5075.67
Encroach Node=5274
       1  4944.7 5075.67
Encroach Node=5046.
       1  4922.3    5066
Encroach Node=4762
       1  4978.9  5018.6
Encroach Node=4747
       1  4978.9  5018.6
Encroach Node=4732
       1  4978.9  5018.6
Encroach Node=4617
       1  4954.6  5044.6
Encroach Node=4497
       1  4964.1  5044.1
Encroach Node=3720
       1  4935.5  5055.5
Encroach Node=3604
       1    4968  5037.6
Encroach Node=3546.5
       1    4968  5037.6
Encroach Node=3489
       1    4968  5037.6
Encroach Node=3393.
       1  4951.3  5061.3
Encroach Node=2181
       1  4964.1  5040.4
Encroach Node=693
       1  4968.3  5034.4
Encroach Node=635
       1  4968.4  5041.3
Encroach Node=628.5
       1  4968.4  5041.3
Encroach Node=622
       1    4980    5045
Encroach Node=565
       1  4847.8  5187.8
BEGIN DESCRIPTION:
FEMA Effective 2007 + LOMR 16-06-1373P
END DESCRIPTION:
Computation Interval=1HOUR
Output Interval=1HOUR
Run HTab= 0
Run UNet= 0
Run PostProcess= 0
UNET Theta= 1
UNET ZTol= 0.02
UNET ZSATol= 0.1
UNET MxIter= 20
UNET MaxInSteps= 20
UNET DtIC= 0
UNET DtMin= 0
UNET MaxCRTS= 20
UNET WFStab= 2
UNET SFStab= 1
UNET WFX= 1
UNET SFX= 1
UNET Convert EG Bridges=-1
UNET Use Existing IB Tables=-1
Instantaneous Interval=1HOUR
Write IC File= 0
IC Time=0
Write Velocity= 0
Write Detailed= 0

--- K120-03-00.p01 (plan) ---

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Plan Title=Effective MP 2016
Short Identifier=Eff+LOMR MP
Geom File=g01
Flow File=f01
Encroach Param=-1 ,0,0, 0
UNET ZSATol= 0.05
UNET MaxInSteps= 0
UNET Convert EG Bridges= 0

--- K120-03-00.f02 (steady flow) ---

Flow Title=Effective Floodway 2016
Version=Version 3.0.1  May 2012
Number of Profiles= 2
Profile Names=1PCT_100yr, 1PCTFloodway_100yrFW
River Rch & RM=K120-03-00,K120-03-00_0006 ,10241
     920     920
River Rch & RM=K120-03-00,K120-03-00_0006 ,8840
     940     940
River Rch & RM=K120-03-00,K120-03-00_0006 ,8810
     990     990
River Rch & RM=K120-03-00,K120-03-00_0006 ,7712
    1010    1010
River Rch & RM=K120-03-00,K120-03-00_0006 ,7089
    1050    1050
River Rch & RM=K120-03-00,K120-03-00_0006 ,5957
    1090    1090
River Rch & RM=K120-03-00,K120-03-00_0006 ,4732
    1140    1140
River Rch & RM=K120-03-00,K120-03-00_0006 ,3489
    1250    1250
Boundary for River Rch & Prof#=K120-03-00,K120-03-00_0006 , 1
Up Type= 0
Dn Type= 3
Dn Slope=.015
Boundary for River Rch & Prof#=K120-03-00,K120-03-00_0006 , 2
Up Type= 0
Dn Type= 1
Dn Known WS=93.67
DSS Import GetInterval= 0
DSS Import GetPeak= 0
DSS Import FillOption= 0

--- K120-03-00.f01 (steady flow) ---

Flow Title=FEMA Effective June 2016
Version=Version 3.0.1  May 2012
Number of Profiles= 4
Profile Names=10PCT_10yr, 2PCT_50yr, 1PCT_100yr, 0.2PCT_500yr
River Rch & RM=K120-03-00,K120-03-00_0006 ,10241
     490     770     920    1410
River Rch & RM=K120-03-00,K120-03-00_0006 ,8840
     500     780     940    1440
River Rch & RM=K120-03-00,K120-03-00_0006 ,8810
     520     820     990    1500
River Rch & RM=K120-03-00,K120-03-00_0006 ,7712
     530     830    1010    1520
River Rch & RM=K120-03-00,K120-03-00_0006 ,7089
     550     860    1050    1560
River Rch & RM=K120-03-00,K120-03-00_0006 ,5957
     560     890    1090    1600
River Rch & RM=K120-03-00,K120-03-00_0006 ,4732
     580     920    1140    1640
River Rch & RM=K120-03-00,K120-03-00_0006 ,3489
     630    1000    1250    1750
Boundary for River Rch & Prof#=K120-03-00,K120-03-00_0006 , 1
Up Type= 0
Dn Type= 3
Dn Slope=.015
Boundary for River Rch & Prof#=K120-03-00,K120-03-00_0006 , 2
Up Type= 0
Dn Type= 3
Dn Slope=.015
Boundary for River Rch & Prof#=K120-03-00,K120-03-00_0006 , 3
Up Type= 0
Dn Type= 3
Dn Slope=.015
Boundary for River Rch & Prof#=K120-03-00,K120-03-00_0006 , 4
Up Type= 0
Dn Type= 3
Dn Slope=.015
DSS Import GetInterval= 0
DSS Import GetPeak= 0
DSS Import FillOption= 0

--- K120-03-00.g01 (geometry) ---

Geom Title=K120-03-00 2016
Version=Version 3.0.1  August 2016

River Reach=K120-03-00      ,K120-03-00_0006
Reach XY= 30
      3093668.65      13957252.5      3093889.56     13957147.11
        3094484.       13957002.      3095149.67     13957148.26
      3095507.66     13957130.58      3095786.31      13957040.3
      3096068.53     13957023.97      3096209.05     13956836.31
      3096587.09     13955953.74      3096756.09     13955718.74
      3096812.35     13955467.38      3096809.75     13954899.68
      3096905.23     13954712.18      3096973.81     13954642.73
      3097081.34     13954607.74       3097131.8     13954523.81
      3097154.36     13954439.61      3097067.52     13954302.94
      3097176.07      13954018.6      3097586.84     13953650.74
      3097670.34     13953475.74      3097908.71     13953239.08
      3098064.36      13952749.1      3098304.81     13952519.93
      3098650.29     13951963.51      3099139.01     13951470.46
      3099585.99     13951342.53      3099770.08     13951313.34
      3099971.36     13951361.41      3100220.93      13951276.7

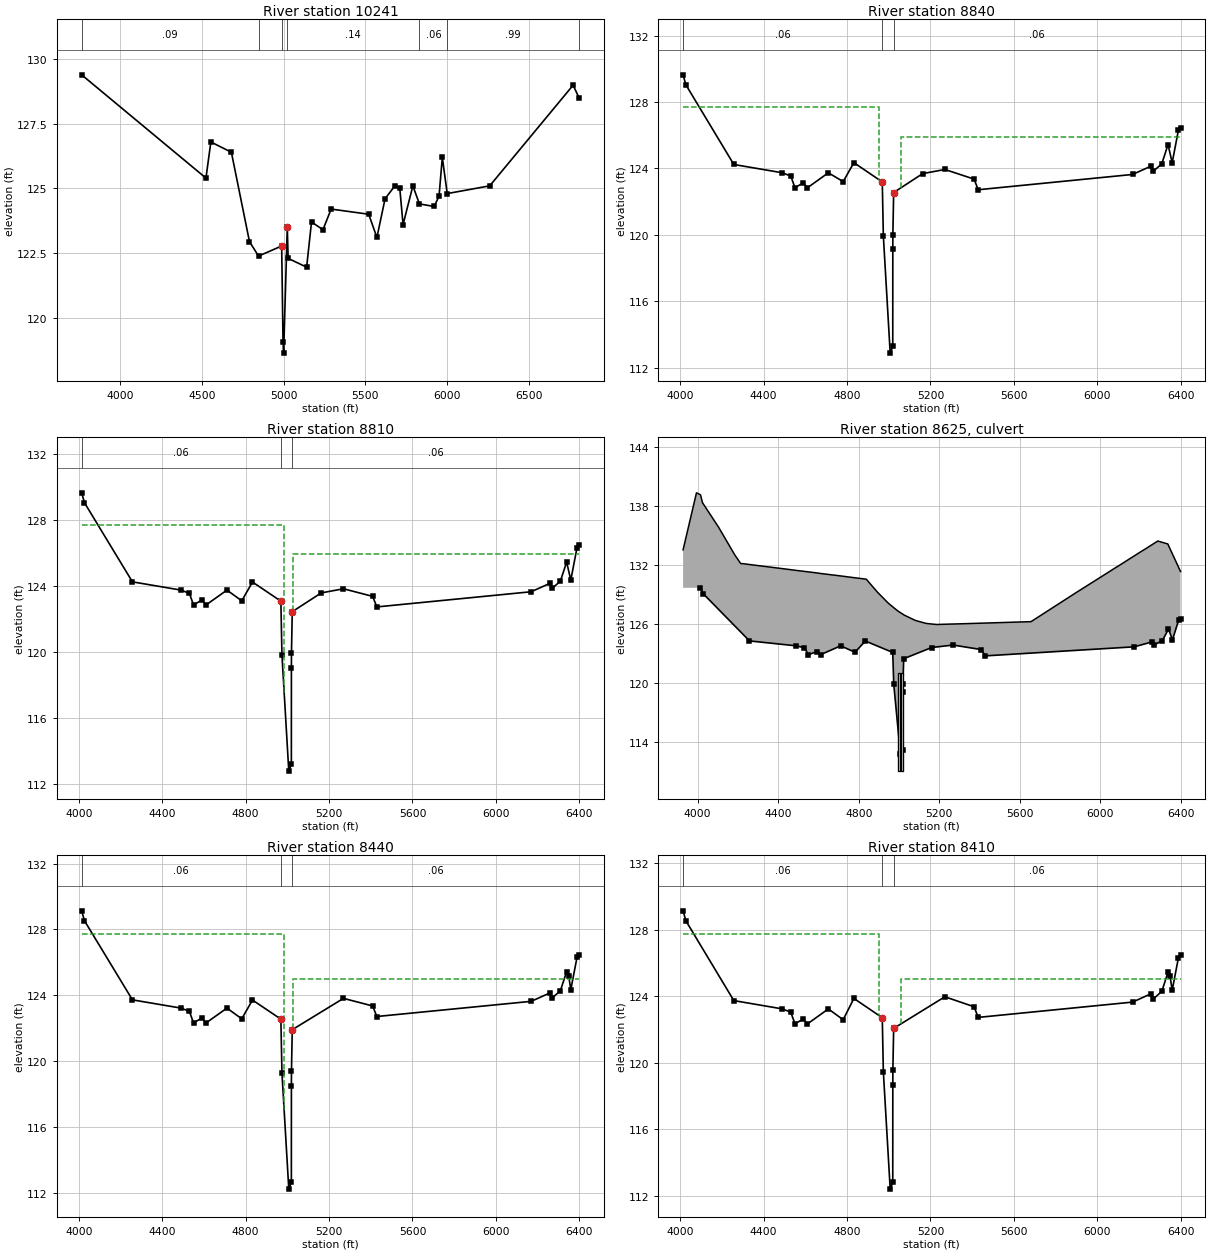
Type RM Length L Ch R = 1 ,10241   ,1351.8,1401,1421.8
BEGIN DESCRIPTION:
Cross Section K120-03-00-X5
Located At: CROSS SECTION
Flows beyond the levee exit stream flow path VRR
END DESCRIPTION:
XS GIS Cut Line= 4
      3093911.46      13958416.7      3093869.88     13957502.27
       3093592.1     13956859.91      3092350.78     13956156.78
#Sta/Elev= 30
  3765.3   129.4  4525.3   125.4  4555.3   126.8  4680.8   126.4  4791.4  122.94
  4846.8  122.38  4988.3  122.77  4996.6  119.07  5000.3  118.62  5022.6  123.49
  5027.9  122.29    5141  121.95  5170.8   123.7  5240.8   123.4  5290.8   124.2
  5520.6     124  5570.6   123.1  5620.6   124.6  5680.6   125.1  5710.6     125
  5730.6   123.6  5790.6   125.1  5830.6   124.4  5920.6   124.3  5950.6   124.7
  5970.6   126.2  6000.6   124.8  6260.6   125.1  6770.6     129  6807.3   128.5
#Mann= 7 ,-1 , 0
  3765.3     .09       0  4846.8      .1       0  4988.3     .05       0
  5022.6     .14       0  5830.6     .06       0  6000.6     .99       0
  6807.3     .99       0
Bank Sta=4988.3,5022.6
XS Rating Curve= 0
Exp/Cntr=.3,.1

Type RM Length L Ch R = 1 ,8840    ,30,30,29
BEGIN DESCRIPTION:
IH45 - XS 4
END DESCRIPTION:
XS GIS Cut Line= 4
      3095093.05      13958107.8      3095018.08      13957637.4
      3095141.47      13956868.4        3095433.      13955776.7
#Sta/Elev= 30
    4014  129.64  4027.4  129.04  4257.4  124.24  4490.5  123.74  4530.5  123.54
  4550.5  122.84  4590.5  123.14  4610.5  122.84  4710.5  123.74  4781.6  123.21
    4833  124.35  4969.1  123.19  4974.3  119.93  5007.1  112.88  5019.4  113.29
  5019.6  119.16  5019.9  120.02  5023.7  122.55  5162.7  123.69  5269.2  123.94
  5409.2  123.36  5429.2  122.72  6169.2  123.64  6259.2  124.15  6269.2  123.84
  6309.2  124.28  6339.2  125.44  6359.2  124.35  6389.2  126.32  6399.2  126.46
#Mann= 3 ,-1 , 0
    4014     .06       0  4969.1     .05       0  5023.7     .06       0
#XS Ineff= 2 , 0
       0    4955  127.71    5058       0  125.91
Permanent Ineff=
       F       F
Bank Sta=4969.1,5023.7
XS Rating Curve= 0
Exp/Cntr=.5,.3

Type RM Length L Ch R = 1 ,8810    ,370,370,370
BEGIN DESCRIPTION:
IH45 - XS 3
Upstream Section of Bridge/Culvert/Weir - See Comment
This road was undre construction at the time of the survey/study.  Channelization may have occured downstream since the study.
END DESCRIPTION:
XS GIS Cut Line= 4
      3095122.04      13958116.7      3095047.08      13957646.4
      3095170.47     13956877.34      3095461.99      13955785.6
#Sta/Elev= 30
    4014  129.64  4027.4  129.04  4257.4  124.24  4490.5  123.74  4530.5  123.54
  4550.5  122.84  4590.5  123.14  4610.5  122.84  4710.5  123.74  4781.6  123.09
    4833  124.23  4969.1  123.07  4974.3  119.81  5007.1  112.76  5019.4  113.17
  5019.6  119.04  5019.9   119.9  5023.7  122.43  5162.7  123.57  5269.2  123.82
  5409.2  123.36  5429.2  122.72  6169.2  123.64  6259.2  124.15  6269.2  123.84
  6309.2  124.28  6339.2  125.44  6359.2  124.35  6389.2  126.32  6399.2  126.46
#Mann= 3 ,-1 , 0
    4014     .06       0  4969.1     .05       0  5023.7     .06       0
#XS Ineff= 2 , 0
       0    4985  127.71    5028       0  125.91
Permanent Ineff=
       F       F
Bank Sta=4969.1,5023.7
XS Rating Curve= 0
Exp/Cntr=.5,.3

Type RM Length L Ch R = 2 ,8625    ,,,
BEGIN DESCRIPTION:
IH45
Structure ID: K120-03-00-S08
END DESCRIPTION:
Bridge Culvert--1,0,-1,-1, 0
Deck Dist Width WeirC Skew NumUp NumDn MinLoCord MaxHiCord MaxSubmerge Is_Ogee
10,356,3,0, 75, 75, , , .95, 0, 0,0,,
  3927.4    3994    4014    4024  4027.4    4104    4184    4214    4224  4257.4
  4437.4  4490.5  4530.5  4550.5  4590.5  4610.5  4710.5  4781.6    4833  4837.7
  4886.7  4893.6 4940.69  4940.8 4940.91  4945.4  4947.6  4969.1  4974.3  4980.1
  4980.8  4981.2  4991.7  5006.9  5007.1  5019.4  5019.6  5019.9  5023.7  5027.9
 5047.09  5047.2 5047.31  5047.5  5080.6    5112  5135.6  5162.7  5189.5  5215.9
  5266.5  5269.4  5369.4  5656.3  5819.4  5876.3  6019.4  6053.4  6069.4  6089.4
  6099.4  6109.4  6129.4  6139.4  6169.4  6199.4  6229.4  6269.4  6286.3  6299.4
  6319.4  6329.4  6336.3  6338.2  6399.2
   133.5   139.3   139.1   138.3  138.19   135.8     133   132.1   132.1  132.01
  131.55  131.41  131.31  131.26  131.16   131.1  130.85  130.66  130.53  130.52
  129.35  129.19  128.21  128.21  128.21  128.12  128.07  127.71  127.62  127.52
  127.51  127.51  127.33  127.12  127.12  126.96  126.96  126.95   126.9  126.85
  126.66  126.66  126.66  126.66  126.33  126.15  126.02  125.96  125.91  125.93
  125.96  125.96  126.02   126.2  128.35   129.1  130.95  131.39   131.6  131.85
  131.98  132.11  132.37   132.5  132.89  133.28  133.66  134.18   134.4  134.32
   134.2  134.14   134.1     134   131.3
                                                                                
                                                                                
                                                                                
                                                                                
                                                                                
                                                                                
                                                                                
                                        
  3927.4    3994    4014    4024  4027.4    4104    4184    4214    4224  4257.4
  4437.4  4490.5  4530.5  4550.5  4590.5  4610.5  4710.5  4781.6    4833  4837.7
  4886.7  4893.6 4940.69  4940.8 4940.91  4945.4  4947.6  4969.1  4974.3  4980.1
  4980.8  4981.2  4991.7  5006.9  5007.1  5019.4  5019.6  5019.9  5023.7  5027.9
 5047.09  5047.2 5047.31  5047.5  5080.6    5112  5135.6  5162.7  5189.5  5215.9
  5266.5  5269.4  5369.4  5656.3  5819.4  5876.3  6019.4  6053.4  6069.4  6089.4
  6099.4  6109.4  6129.4  6139.4  6169.4  6199.4  6229.4  6269.4  6286.3  6299.4
  6319.4  6329.4  6336.3  6338.2  6399.2
   133.5   139.3   139.1   138.3  138.19   135.8     133   132.1   132.1  132.01
  131.55  131.41  131.31  131.26  131.16   131.1  130.85  130.66  130.53  130.52
  129.35  129.19  128.21  128.21  128.21  128.12  128.07  127.71  127.62  127.52
  127.51  127.51  127.33  127.12  127.12  126.96  126.96  126.95   126.9  126.85
  126.66  126.66  126.66  126.66  126.33  126.15  126.02  125.96  125.91  125.93
  125.96  125.96  126.02   126.2  128.35   129.1  130.95  131.39   131.6  131.85
  131.98  132.11  132.37   132.5  132.89  133.28  133.66  134.18   134.4  134.32
   134.2  134.14   134.1     134   131.3
                                                                                
                                                                                
                                                                                
                                                                                
                                                                                
                                                                                
                                                                                
                                        
BR Coef= 1 , 1 , 0 ,1.25, 0 ,,,.8,-1,2,0,
WSPro=,,,, 1 ,,,, 0 ,,,, 0 ,,,,-1 ,-1 ,-1 , 0 , 0 , 0 , 0 , 0
Culvert=2,10,10,356,.015,.2,1,8,3,111,5000.9,109.94,5000.9,Culvert #1  , 0 ,10
Culvert Bottom n=.015
Culvert=2,10,10,356,.015,.2,1,8,1,111.02,5013.6,110.01,5013.6,Culvert #2  , 0 ,10
Culvert Bottom n=.015
BC Design=,, 0 ,, 0 ,,,,,,
BC HTab HWMax=133.54

Type RM Length L Ch R = 1 ,8440    ,30,30,31
BEGIN DESCRIPTION:
IH45 - XS 2
Downstream Section of Bridge/Culvert/Weir - See Comment
This road was undre construction at the time of the survey/study.  Channelization may have occured downstream since the study.
END DESCRIPTION:
XS GIS Cut Line= 5
      3095429.28      13958073.5      3095398.74     13957825.83
      3095533.91     13956866.12      3095580.06     13956279.53
      3095669.67      13955792.2
#Sta/Elev= 30
    4014  129.13  4027.4  128.53  4257.4  123.73  4490.5  123.23  4530.5  123.03
  4550.5  122.33  4590.5  122.63  4610.5  122.33  4710.5  123.23  4781.6  122.58
    4833  123.72  4969.1  122.56  4974.3   119.3  5007.1  112.25  5019.4  112.66
  5019.6  118.53  5019.9  119.39  5023.7  121.92  5269.2  123.82  5409.2  123.36
  5429.2  122.72  6169.2  123.64  6259.2  124.15  6269.2  123.84  6309.2  124.28
  6339.2  125.44  6349.2  125.18  6359.2  124.35  6389.2  126.32  6399.2  126.46
#Mann= 3 ,-1 , 0
    4014     .06       0  4969.1     .05       0  5023.7     .06       0
#XS Ineff= 2 , 0
       0    4985  127.71    5028       0     125
Permanent Ineff=
       F       F
Bank Sta=4969.1,5023.7
XS Rating Curve= 0
Exp/Cntr=.5,.3

Type RM Length L Ch R = 1 ,8410    ,789.8,698,684.8
BEGIN DESCRIPTION:
IH45 - XS 1
END DESCRIPTION:
XS GIS Cut Line= 5
      3095458.73      13958067.3      3095428.18      13957819.6
      3095563.35      13956859.8       3095609.5      13956273.3
      3095699.11       13955786.
#Sta/Elev= 30
    4014  129.13  4027.4  128.53  4257.4  123.73  4490.5  123.23  4530.5  123.03
  4550.5  122.33  4590.5  122.63  4610.5  122.33  4710.5  123.23  4781.6  122.58
    4833  123.86  4969.1   122.7  4974.3  119.44  5007.1  112.39  5019.4   112.8
  5019.6  118.67  5019.9  119.53  5023.7  122.06  5269.2  123.96  5409.2  123.36
  5429.2  122.72  6169.2  123.64  6259.2  124.15  6269.2  123.84  6309.2  124.28
  6339.2  125.44  6349.2  125.18  6359.2  124.35  6389.2  126.32  6399.2  126.46
#Mann= 3 ,-1 , 0
    4014     .06       0  4969.1     .05       0  5023.7     .06       0
#XS Ineff= 2 , 0
       0    4955  127.71    5058       0     125
Permanent Ineff=
       F       F
Bank Sta=4969.1,5023.7
XS Rating Curve= 0
Exp/Cntr=.3,.1

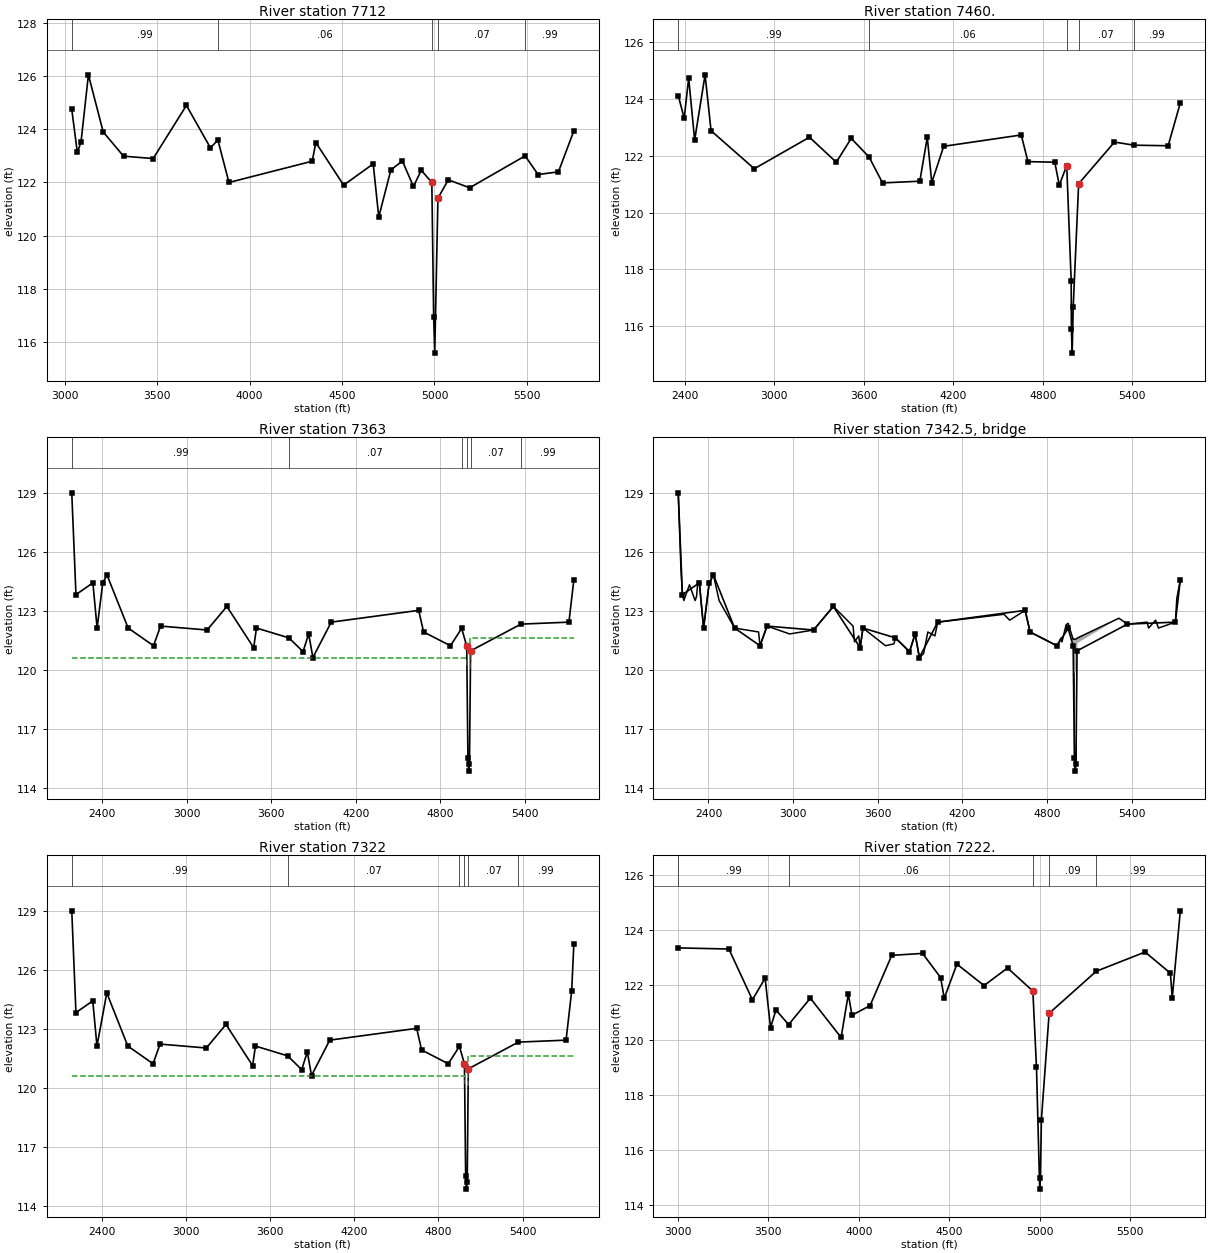
Type RM Length L Ch R = 1 ,7712    ,318,252,219
BEGIN DESCRIPTION:
Cross Section K120-03-00-X4
END DESCRIPTION:
XS GIS Cut Line= 4
      3097305.76     13958504.26      3096327.25     13957070.11
      3096006.01     13956806.84      3095605.97      13956410.1
#Sta/Elev= 30
  3038.7  124.75  3068.7  123.13  3088.7  123.52  3128.7  126.05  3208.7   123.9
  3318.7  122.99  3478.7   122.9  3658.7   124.9  3788.7   123.3  3828.7   123.6
  3888.7     122  4338.7   122.8  4358.7   123.5  4508.7   121.9  4668.7   122.7
  4698.7   120.7  4764.1  122.47  4826.2  122.81  4886.5  121.85  4928.5  122.46
  4985.7     122  4995.6  116.95  5001.4  115.58  5018.7  121.41  5074.9   122.1
  5190.2   121.8  5490.2     123  5560.2   122.3  5670.2   122.4 5753.62  123.94
#Mann= 5 ,-1 , 0
  3038.7     .99       0  3828.7     .06       0  4985.7    .055       0
  5018.7     .07       0  5490.2     .99       0
Bank Sta=4985.7,5018.7
XS Rating Curve= 0
Exp/Cntr=.3,.1

Type RM Length L Ch R = 1 ,7460.   ,98,97,96
BEGIN DESCRIPTION:
PRIVATE DRIVE 650' US OF SPRING CYPRESS - XS 4
Interpolated channel - LIDAR overbanks
END DESCRIPTION:
XS GIS Cut Line= 4
 3098094.6591958  13958545.72034      3096572.71     13956801.27
      3095990.95     13956617.17       3095606.2      13956400.8
#Sta/Elev= 30
  2355.5  124.13  2395.5  123.33  2425.5  124.75  2465.5  122.56  2535.5  124.86
  2575.5  122.89  2865.5  121.55  3235.5  122.66  3415.5  121.78  3515.5  122.62
  3635.5  121.96  3725.5  121.05  3975.5  121.11  4025.5  122.66  4055.5  121.06
  4135.5  122.34  4655.5  122.74  4700.5   121.8  4880.5  121.78  4910.5  120.97
  4960.5  121.66  4990.5  117.59 4991.83   115.9 4997.03  115.05 5003.86  116.66
  5040.5  121.02  5280.7  122.49  5410.7  122.38  5640.7  122.36  5722.2  123.87
#Mann= 5 ,-1 , 0
  2355.5     .99       0  3635.5     .06       0  4960.5    .055       0
  5040.5     .07       0  5410.7     .99       0
Bank Sta=4960.5,5040.5
XS Rating Curve= 0
Exp/Cntr=.5,.3

Type RM Length L Ch R = 1 ,7363    ,41,41,41
BEGIN DESCRIPTION:
PRIVATE DRIVE 650' US OF SPRING CYPRESS - XS 3
Upstream Section of Bridge/Culvert/Weir
END DESCRIPTION:
XS GIS Cut Line= 4
      3098237.96     13958582.06      3096604.26      13956709.5
      3096022.49      13956525.4      3095617.16      13956298.3
#Sta/Elev= 30
  2185.6     129  2215.3  123.82  2335.3  124.42  2365.3  122.12  2405.3  124.42
  2435.3  124.82  2585.3  122.12  2765.3  121.22  2815.3  122.22  3145.3  122.02
  3285.3  123.22  3475.3  121.12  3495.3  122.12  3725.3  121.62  3825.3  120.92
  3865.3  121.82  3895.3  120.62  4025.3  122.42  4645.3  123.02  4680.3  121.92
  4870.3  121.22  4950.1   122.1  4985.8  121.21  4994.5  115.51  4999.5  114.84
  5005.4  115.18  5013.4  120.96  5370.5  122.32  5710.5  122.42 5745.47  124.57
#Mann= 6 ,-1 , 0
  2185.6     .99       0  3725.3     .07       0  4950.1    .045       0
  4985.8     .06       0  5013.4     .07       0  5370.5     .99       0
#XS Ineff= 2 , 0
       0 4987.38   120.6 5012.17       0   121.6
Permanent Ineff=
       F       F
Bank Sta=4985.8,5013.4
XS Rating Curve= 0
Exp/Cntr=.5,.3

Type RM Length L Ch R = 3 ,7342.5  ,,,
BEGIN DESCRIPTION:
PRIVATE DRIVE 650' US OF SPRING CYPRESS
Structure ID: K120-03-00-S7A
END DESCRIPTION:
Bridge Culvert--1,0,-1,-1, 0
Deck Dist Width WeirC Skew NumUp NumDn MinLoCord MaxHiCord MaxSubmerge Is_Ogee
10,14,2.6,0, 60, 60, , , .95, 0, 0,0,,
  2185.6  2205.3  2215.3  2225.3  2265.3  2305.3  2315.3  2325.3  2335.3  2365.3
  2405.3  2435.3  2475.3  2585.3  2755.3  2765.3  2815.3  2975.3  3145.3  3285.3
  3425.3  3435.3  3465.3  3475.3  3495.3  3655.3  3715.3  3725.3  3825.3  3865.3
  3895.3  3925.3  3955.3  4005.3  4025.3  4495.3  4535.3  4645.3  4680.3  4870.3
  4900.3  4906.3    4936  4950.1  4971.9  4985.8  4987.4  5000.6 5011.98  5013.4
  5017.4  5310.1  5370.5  5510.5  5520.5  5570.5  5590.5  5710.5  5720.5 5745.47
     129  125.02  123.82  123.52  124.32  123.52  123.72  124.52  124.42  122.12
  124.42  124.82  123.52  122.12  121.92  121.22  122.22  121.82  122.02  123.22
  122.22  121.42  121.72  121.12  122.12  121.22  121.32  121.62  120.92  121.82
  120.62  120.82  121.92  121.72  122.42  122.82  122.52  123.02  121.92  121.22
  121.62  121.41  122.29  122.36  121.86  121.54  121.56  121.55  121.59   121.6
  121.62  122.62  122.32  122.42  122.12  122.52  122.12  122.42  123.62  124.57
     129  125.02  123.82  123.52  124.32  123.52  123.72  124.52  124.42  122.12
  124.42  124.82  123.52  122.12  121.92  121.22  122.22  121.82  122.02  123.22
  122.22  121.42  121.72  121.12  122.12  121.22  121.32  121.62  120.92  121.82
  120.62  120.82  121.92  121.72  122.42  122.82  122.52  123.02  121.92  121.22
  121.62  121.41  122.29   122.1   121.8  121.21  119.94  119.85  119.89  120.96
  121.36  122.62  122.32  122.42  122.12  122.52  122.12  122.42  123.62  124.57
  2185.6  2205.3  2215.3  2225.3  2265.3  2305.3  2315.3  2325.3  2335.3  2365.3
  2405.3  2435.3  2475.3  2585.3  2755.3  2765.3  2815.3  2975.3  3145.3  3285.3
  3425.3  3435.3  3465.3  3475.3  3495.3  3655.3  3715.3  3725.3  3825.3  3865.3
  3895.3  3925.3  3955.3  4005.3  4025.3  4495.3  4535.3  4645.3  4680.3  4870.3
  4900.3  4906.3    4936  4971.9  4985.8  4987.4  5003.7 5012.09  5013.4  5017.4
  5310.1  5510.5  5520.5  5570.5  5590.5  5710.5  5720.5  5740.5  5750.5 5765.99
     129  125.02  123.82  123.52  124.32  123.52  123.72  124.52  124.42  122.12
  124.42  124.82  123.52  122.12  121.92  121.22  122.22  121.82  122.02  123.22
  122.22  121.42  121.72  121.12  122.12  121.22  121.32  121.62  120.92  121.82
  120.62  120.82  121.92  121.72  122.42  122.82  122.52  123.02  121.92  121.22
  121.62  121.41  122.29  121.86  121.54  121.56  121.56  121.59   121.6  121.62
  122.62  122.42  122.12  122.52  122.12  122.42  123.62  124.22  124.92  127.31
     129  125.02  123.82  123.52  124.32  123.52  123.72  124.52  124.42  122.12
  124.42  124.82  123.52  122.12  121.92  121.22  122.22  121.82  122.02  123.22
  122.22  121.42  121.72  121.12  122.12  121.22  121.32  121.62  120.92  121.82
  120.62  120.82  121.92  121.72  122.42  122.82  122.52  123.02  121.92  121.22
  121.62  121.41  122.29   121.8  121.21  119.94  119.86   119.9  120.96  121.36
  122.62  122.42  122.12  122.52  122.12  122.42  123.62  124.22  124.92  127.31
Pier Skew, UpSta & Num, DnSta & Num=  ,4994.5, 2 ,4994.5, 2 , 0 , 0 , 0 ,,
       1       1
   114.4  120.85
       1       1
   114.5  120.95
Pier Skew, UpSta & Num, DnSta & Num=  ,5005.4, 2 ,5005.4, 2 , 0 , 0 , 0 ,,
       1       1
  114.13  120.87
       1       1
  114.23  120.97
BR Coef= 1 , 1 , 0 ,1.25, 0 ,,,.8,0,2,0,
WSPro=,,,, 1 ,,,, 0 ,,,, 0 ,,,,-1 ,-1 ,-1 , 0 , 0 , 0 , 0 , 0
BC Design=,, 0 ,, 0 ,,,,,,
BC HTab HWMax=133.42

Type RM Length L Ch R = 1 ,7322    ,101,100,99
BEGIN DESCRIPTION:
PRIVATE DRIVE 650' US OF SPRING CYPRESS - XS 2
Downstream Section of Bridge/Culvert/Weir
END DESCRIPTION:
XS GIS Cut Line= 4
      3098260.51     13958549.54      3096623.12     13956672.76
      3096037.97     13956487.59      3095622.68       13956255.
#Sta/Elev= 30
  2185.6     129  2215.3  123.82  2335.3  124.42  2365.3  122.12  2435.3  124.82
  2585.3  122.12  2765.3  121.22  2815.3  122.22  3145.3  122.02  3285.3  123.22
  3475.3  121.12  3495.3  122.12  3725.3  121.62  3825.3  120.92  3865.3  121.82
  3895.3  120.62  4025.3  122.42  4645.3  123.02  4680.3  121.92  4870.3  121.22
  4950.1   122.1  4985.8  121.21  4994.5  115.51  4999.5  114.84  5005.4  115.18
  5013.4  120.96  5370.5  122.32  5710.5  122.42  5750.5  124.92 5765.99  127.31
#Mann= 6 ,-1 , 0
  2185.6     .99       0  3725.3     .07       0  4950.1    .045       0
  4985.8     .06       0  5013.4     .07       0  5370.5     .99       0
#XS Ineff= 2 , 0
       0 4987.38   120.6 5012.17       0   121.6
Permanent Ineff=
       F       F
Bank Sta=4985.8,5013.4
XS Rating Curve= 0
Exp/Cntr=.5,.3

Type RM Length L Ch R = 1 ,7222.   ,80,99,104
BEGIN DESCRIPTION:
PRIVATE DRIVE 650' US OF SPRING CYPRESS - XS 1
PRIVATE DRIVE 360' US OF SPRING CYPRESS - XS 4
Interpolated channel - LIDAR overbanks
END DESCRIPTION:
XS GIS Cut Line= 4
  3097981.043944  13957604.63326      3096631.37     13956571.54
      3096049.61     13956387.43      3095644.28     13956160.38
#Sta/Elev= 30
  3002.2  123.36  3282.2  123.32  3412.2  121.47  3482.2  122.26  3512.2  120.46
  3542.2   121.1  3612.2  120.57  3732.2  121.53  3902.2   120.1  3942.2  121.68
  3962.2  120.91  4062.2  121.26  4182.2  123.09  4352.2  123.16  4452.2  122.28
  4472.2  121.53  4542.2  122.77  4692.2  121.99  4821.9  122.63  4961.9  121.79
  4981.9  119.01 4999.65  114.58 5003.92  114.97 5008.95   117.1  5051.9  120.98
  5312.1  122.51  5582.1  123.21  5722.1  122.44  5732.1  121.54  5776.7  124.71
#Mann= 5 ,-1 , 0
  3002.2     .99       0  3612.2     .06       0  4961.9    .055       0
  5051.9     .09       0  5312.1     .99       0
Bank Sta=4961.9,5051.9
XS Rating Curve= 0
Exp/Cntr=.5,.3

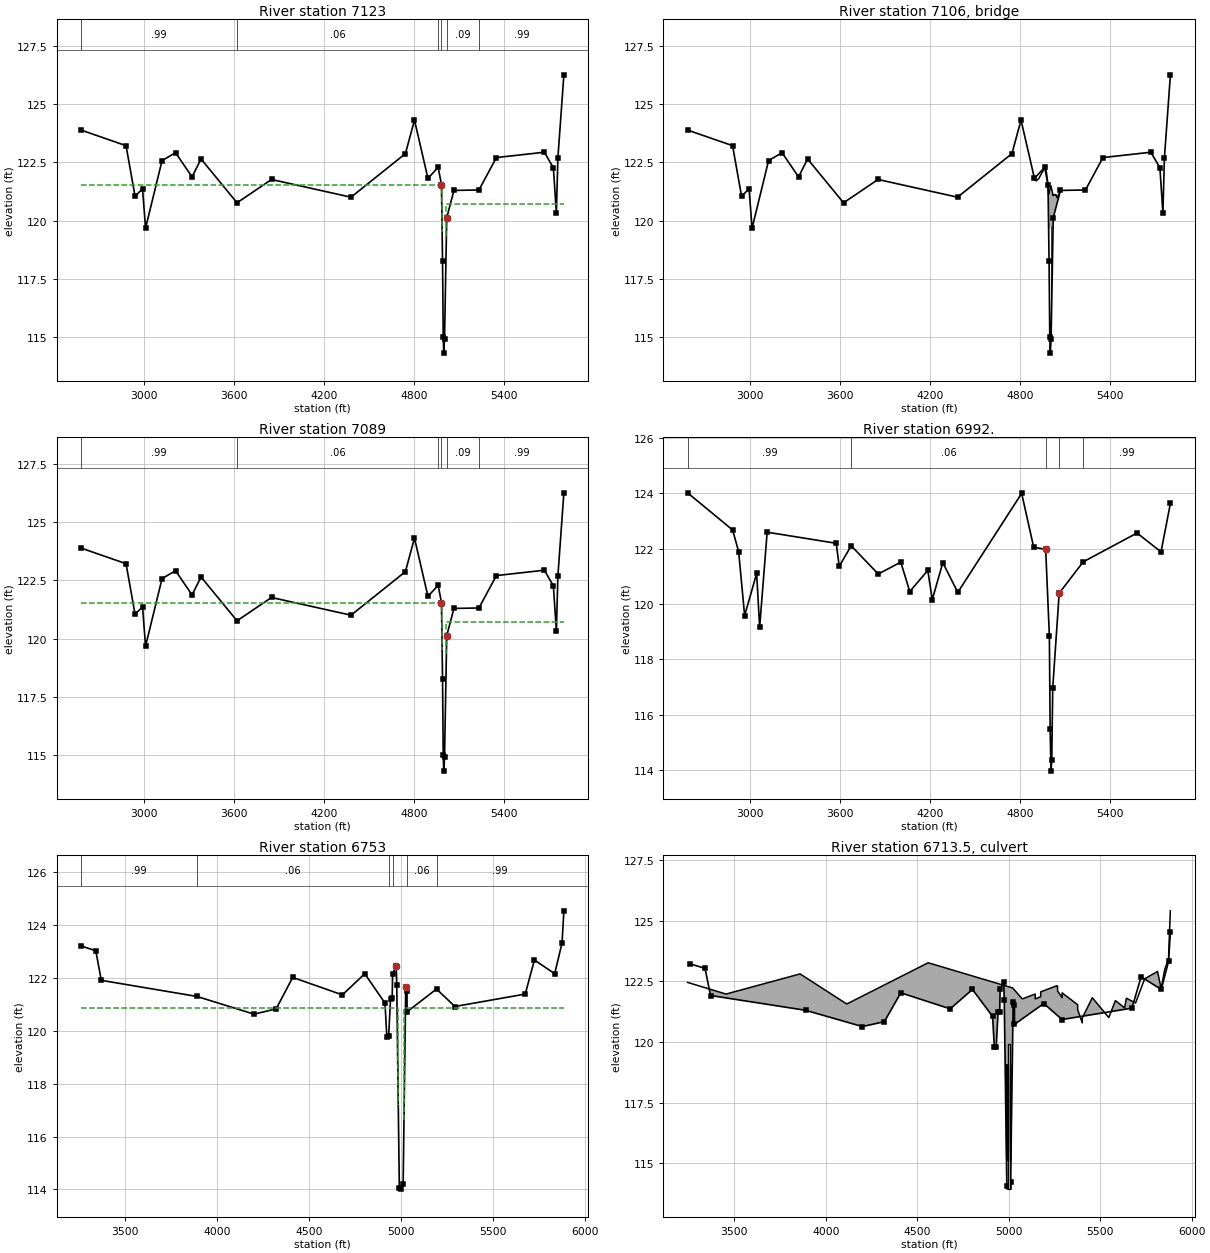
Type RM Length L Ch R = 1 ,7123    ,34,34,34
BEGIN DESCRIPTION:
PRIVATE DRIVE 360' US OF SPRING CYPRESS - XS 3
Upstream Section of Bridge/Culvert/Weir
END DESCRIPTION:
XS GIS Cut Line= 4
       3098624.9       13957327.      3096633.06     13956484.29
      3096169.12     13956307.55      3095646.07      13956107.5
#Sta/Elev= 30
  2581.3  123.89  2881.3  123.22  2941.3  121.05  2991.3  121.37  3011.3  119.68
  3121.3  122.58  3211.3  122.92  3321.3  121.88  3381.3  122.65  3621.3  120.77
  3851.3  121.77  4381.3  121.01  4744.2  122.88  4804.4  124.32  4894.1  121.82
  4962.3  122.29  4984.5  121.55  4991.6  118.28  4996.2  115.03  4999.8  114.32
  5004.8  114.91  5019.5  120.13  5067.5   121.3  5234.4  121.32  5350.6  122.71
  5670.6  122.94  5730.6  122.27  5750.6  120.33  5760.6  122.69  5800.6  126.26
#Mann= 6 ,-1 , 0
  2581.3     .99       0  3621.3     .06       0  4962.3    .045       0
  4984.5    .055       0  5019.5     .09       0  5234.4     .99       0
#XS Ineff= 2 , 0
       0 4988.92  121.54 5017.29       0   120.7
Permanent Ineff=
       F       F
Bank Sta=4984.5,5019.5
XS Rating Curve= 0
Exp/Cntr=.5,.3

Type RM Length L Ch R = 3 ,7106    ,,,
BEGIN DESCRIPTION:
PRIVATE DRIVE 360' US OF SPRING CYPRESS
Structure ID: K120-03-00-S7
END DESCRIPTION:
Bridge Culvert--1,0,-1,-1, 0
Deck Dist Width WeirC Skew NumUp NumDn MinLoCord MaxHiCord MaxSubmerge Is_Ogee
10,14,2.6,0, 33, 33, , , .95, 0, 0,0,,
  4894.1  4904.9  4922.2  4936.4  4962.3  4962.4  4964.9  4970.9  4974.9  4984.5
  4984.9 4988.91    4989    4991  4991.6  4995.4  4996.2  4999.8    5003  5004.4
  5004.8  5005.6  5010.7  5016.3 5017.19  5017.3  5018.2  5018.3  5019.5  5033.8
  5037.1  5044.9  5067.5
   121.8  121.71   121.8  121.97  122.27  122.27   122.3  122.23  122.03  121.54
  121.36  121.14  121.15  121.22  121.23  121.31  121.32   121.4  121.46  121.49
  121.48  121.45   121.3  121.14  121.11  121.11  121.08   121.1   121.1  121.12
  121.12  120.99  121.29
                                                                                
                  119.45  119.51  119.52   119.6  119.61  119.69  119.75  119.78
  119.77  119.74  119.59  119.43   119.4
                        
  4894.1  4904.9  4922.2  4936.4  4962.3  4962.4  4964.9  4970.9  4974.9  4984.5
  4984.9 4988.91    4989    4991  4991.6  4995.4  4996.2  4999.8    5003  5004.4
  5004.8  5005.6  5010.7  5016.3 5017.19  5017.3  5018.2  5018.3  5019.5  5033.8
  5037.1  5044.9  5067.5
   121.8  121.71   121.8  121.97  122.27  122.27   122.3  122.23  122.03  121.54
  121.36  121.14  121.15  121.22  121.23  121.31  121.32   121.4  121.46  121.49
  121.48  121.45   121.3  121.14  121.11  121.11  121.08   121.1   121.1  121.12
  121.12  120.99  121.29
                                                                                
                  119.45  119.51  119.52   119.6  119.61  119.69  119.75  119.78
  119.77  119.74  119.59  119.43   119.4
                        
Pier Skew, UpSta & Num, DnSta & Num=  ,5004.8, 2 ,5004.8, 2 , 0 , 0 , 0 ,,
       1       1
  113.78  120.78
       1       1
  114.06  121.06
BR Coef= 1 , 1 , 1 ,1.25, 0 ,,,.8,0,2,0,
WSPro=,,,, 1 ,,,, 0 ,,,, 0 ,,,,-1 ,-1 ,-1 , 0 , 0 , 0 , 0 , 0
BC Design=,, 0 ,, 0 ,,,,,,
BC HTab HWMax=126.02

Type RM Length L Ch R = 1 ,7089    ,96,97,98
BEGIN DESCRIPTION:
PRIVATE DRIVE 360' US OF SPRING CYPRESS - XS 2
Downstream Section of Bridge/Culvert/Weir
END DESCRIPTION:
XS GIS Cut Line= 4
       3098631.8       13957285.      3096646.97     13956453.16
      3096181.15      13956275.7        3095656.      13956074.4
#Sta/Elev= 30
  2581.3  123.89  2881.3  123.22  2941.3  121.05  2991.3  121.37  3011.3  119.68
  3121.3  122.58  3211.3  122.92  3321.3  121.88  3381.3  122.65  3621.3  120.77
  3851.3  121.77  4381.3  121.01  4744.2  122.88  4804.4  124.32  4894.1  121.82
  4962.3  122.29  4984.5  121.55  4991.6  118.28  4996.2  115.03  4999.8  114.32
  5004.8  114.91  5019.5  120.13  5067.5   121.3  5234.4  121.32  5350.6  122.71
  5670.6  122.94  5730.6  122.27  5750.6  120.33  5760.6  122.69  5800.6  126.26
#Mann= 6 ,-1 , 0
  2581.3     .99       0  3621.3     .06       0  4962.3    .045       0
  4984.5    .055       0  5019.5     .09       0  5234.4     .99       0
#XS Ineff= 2 , 0
       0 4988.92  121.54 5017.29       0   120.7
Permanent Ineff=
       F       F
Bank Sta=4984.5,5019.5
XS Rating Curve= 0
Exp/Cntr=.5,.3

Type RM Length L Ch R = 1 ,6992.   ,213,239,244
BEGIN DESCRIPTION:
PRIVATE DRIVE 360' US OF SPRING CYPRESS - XS 1
SPRING CYPRESS RD - XS 4
Interpolated channel - LIDAR overbanks
END DESCRIPTION:
XS GIS Cut Line= 4
      3098650.18     13957247.58      3096684.25     13956364.26
      3096218.42     13956186.81      3095693.28     13955985.54
#Sta/Elev= 30
  2586.3  124.01  2886.3  122.67  2926.3  121.89  2966.3  119.58  3046.3   121.1
  3066.3  119.16  3116.3  122.59  3576.3  122.19  3596.3  121.36  3676.3   122.1
  3856.3  121.08  4006.3  121.51  4066.3  120.45  4186.3  121.21  4216.3  120.16
  4286.3  121.49  4386.3  120.42  4811.6  123.99  4891.6  122.05  4971.6  121.97
  4996.2  118.85 5001.29   115.5 5007.08  113.97 5012.12  114.37 5018.59  116.97
  5061.6  120.39  5221.6  121.52    5580  122.56    5740  121.88  5802.4  123.63
#Mann= 5 ,-1 , 0
  2586.3     .99       0  3676.3     .06       0  4971.6    .055       0
  5061.6     .06       0  5221.6     .99       0
#XS Ineff= 2 , 0
         3117.08  121.27
Permanent Ineff=
       F       F
Bank Sta=4971.6,5061.6
XS Rating Curve= 0
Exp/Cntr=.5,.3

Type RM Length L Ch R = 1 ,6753    ,100,100,100
BEGIN DESCRIPTION:
SPRING CYPRESS RD - XS 3
Upstream Section of Bridge/Culvert/Weir
END DESCRIPTION:
XS GIS Cut Line= 4
      3098042.99      13956920.3      3096721.84     13956146.31
      3096139.42     13955853.38      3095723.85      13955708.7
#Sta/Elev= 30
  3260.3  123.21  3340.3  123.03  3370.3  121.91  3890.3   121.3  4200.3  120.63
  4320.3  120.83  4410.3  122.02  4680.3  121.36  4801.8  122.16  4911.8  121.05
  4921.8  119.77  4931.8   119.8  4941.9  121.21  4950.9  121.23  4953.1  122.16
  4972.7  122.46  4975.7  121.74  4989.7  114.06    5000  114.01  5010.5  114.22
  5024.5  121.66  5031.5  121.52  5031.7  120.72  5191.8  121.58  5291.8  120.92
  5673.8  121.39  5723.8  122.68  5833.8  122.16  5873.8  123.32  5883.8  124.54
#Mann= 6 ,-1 , 0
  3260.3     .99       0  3890.3     .06       0  4931.8    .045       0
  4953.1    .013       0  5031.7     .06       0  5191.8     .99       0
#XS Ineff= 2 , 0
       0    4984  120.85    5015       0  120.85
Permanent Ineff=
       F       F
Bank Sta=4972.7,5024.5
XS Rating Curve= 0
Exp/Cntr=.5,.3

Type RM Length L Ch R = 2 ,6713.5  ,,,
BEGIN DESCRIPTION:
SPRING CYPRESS RD
Structure ID: K120-03-00-S2
END DESCRIPTION:
Bridge Culvert--1,0,-1,-1, 0
Deck Dist Width WeirC Skew NumUp NumDn MinLoCord MaxHiCord MaxSubmerge Is_Ogee
2,96,3,0, 32, 32, , , .95, 0, ,,,
    3245    3455    3860    4115    4560    5022    5074 5144.99    5145    5175
 5175.01    5262 5266.99    5267    5292 5292.01 5376.99    5377    5402 5402.01
    5457    5547  5583.3  5633.3  5643.3  5693.3  5743.3  5813.3  5833.3  5853.3
  5873.3  5883.3
  122.45  121.97   122.8  121.56  123.26  122.22  121.77  121.97  121.77  121.86
  122.06  122.31   122.3   122.1  121.82  122.02  121.53  121.33  120.78  120.98
  121.82     121   121.7   121.4   121.8   121.6   122.6   122.9   122.2     123
   123.4   125.4
                                                                                
                                                                                
                                                                                
                
    3245    3455    3860    4115    4560    5022    5074 5144.99    5145    5175
 5175.01    5262 5266.99    5267    5292 5292.01 5376.99    5377    5402 5402.01
    5457    5547  5583.3  5633.3  5643.3  5693.3  5743.3  5813.3  5833.3  5853.3
  5873.3  5883.3
  122.45  121.97   122.8  121.56  123.26  122.22  121.77  121.97  121.77  121.86
  122.06  122.31   122.3   122.1  121.82  122.02  121.53  121.33  120.78  120.98
  121.82     121   121.7   121.4   121.8   121.6   122.6   122.9   122.2     123
   123.4   125.4
                                                                                
                                                                                
                                                                                
                
BR Coef= 1 , 1 , 0 ,1.25, 0 ,,,.8,0,2,0,
WSPro=,,,, 1 ,,,, 0 ,,,, 0 ,,,,-1 ,-1 ,-1 , 0 , 0 , 0 , 0 , 0
Culvert=1,4,,96,.013,.2,1,1,2,115.08,4989.7,115.01,4989.7,Culvert #1  , 0 ,2
Culvert Bottom n=.013
Culvert=2,6,9,96,.013,.2,1,10,2,113.93,5000,114.32,5000,Culvert #2  , 0 ,2
Culvert Bottom n=.013
Culvert=1,4,,96,.013,.2,1,1,2,115.07,5010.5,115.03,5010.5,Culvert #3  , 0 ,2
Culvert Bottom n=.013
BC Design=,, 0 ,, 0 ,,,,,,
BC HTab HWMax=125.44