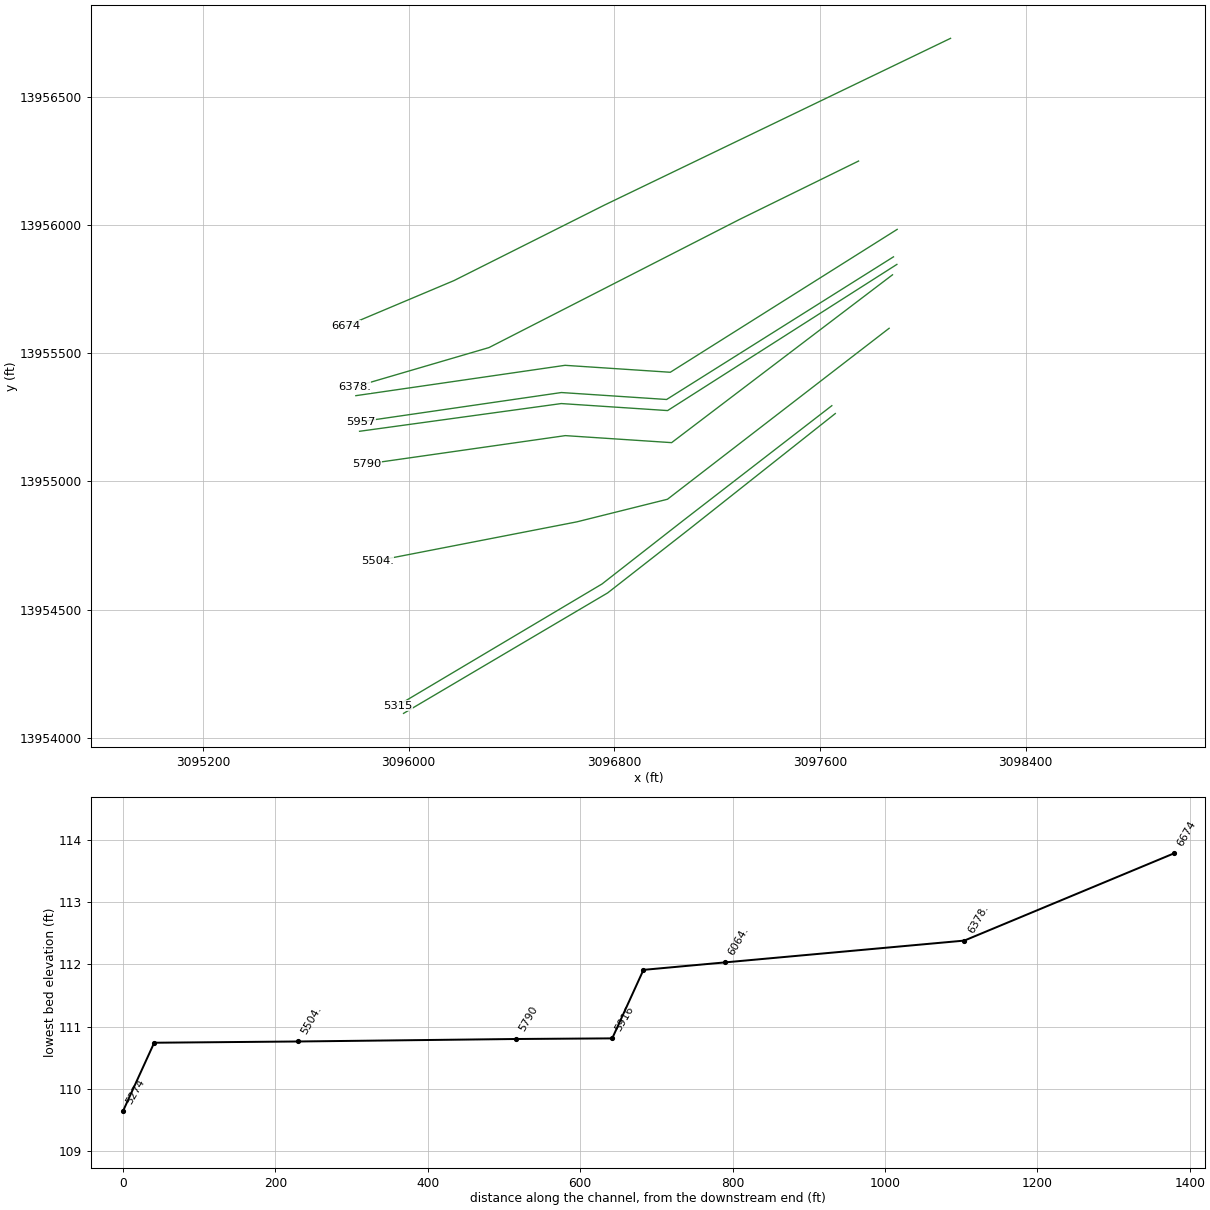
HEC-RAS study K120-03-00.prj: K120-03-00

--- K120-03-00.g01 (geometry) --- (continued)

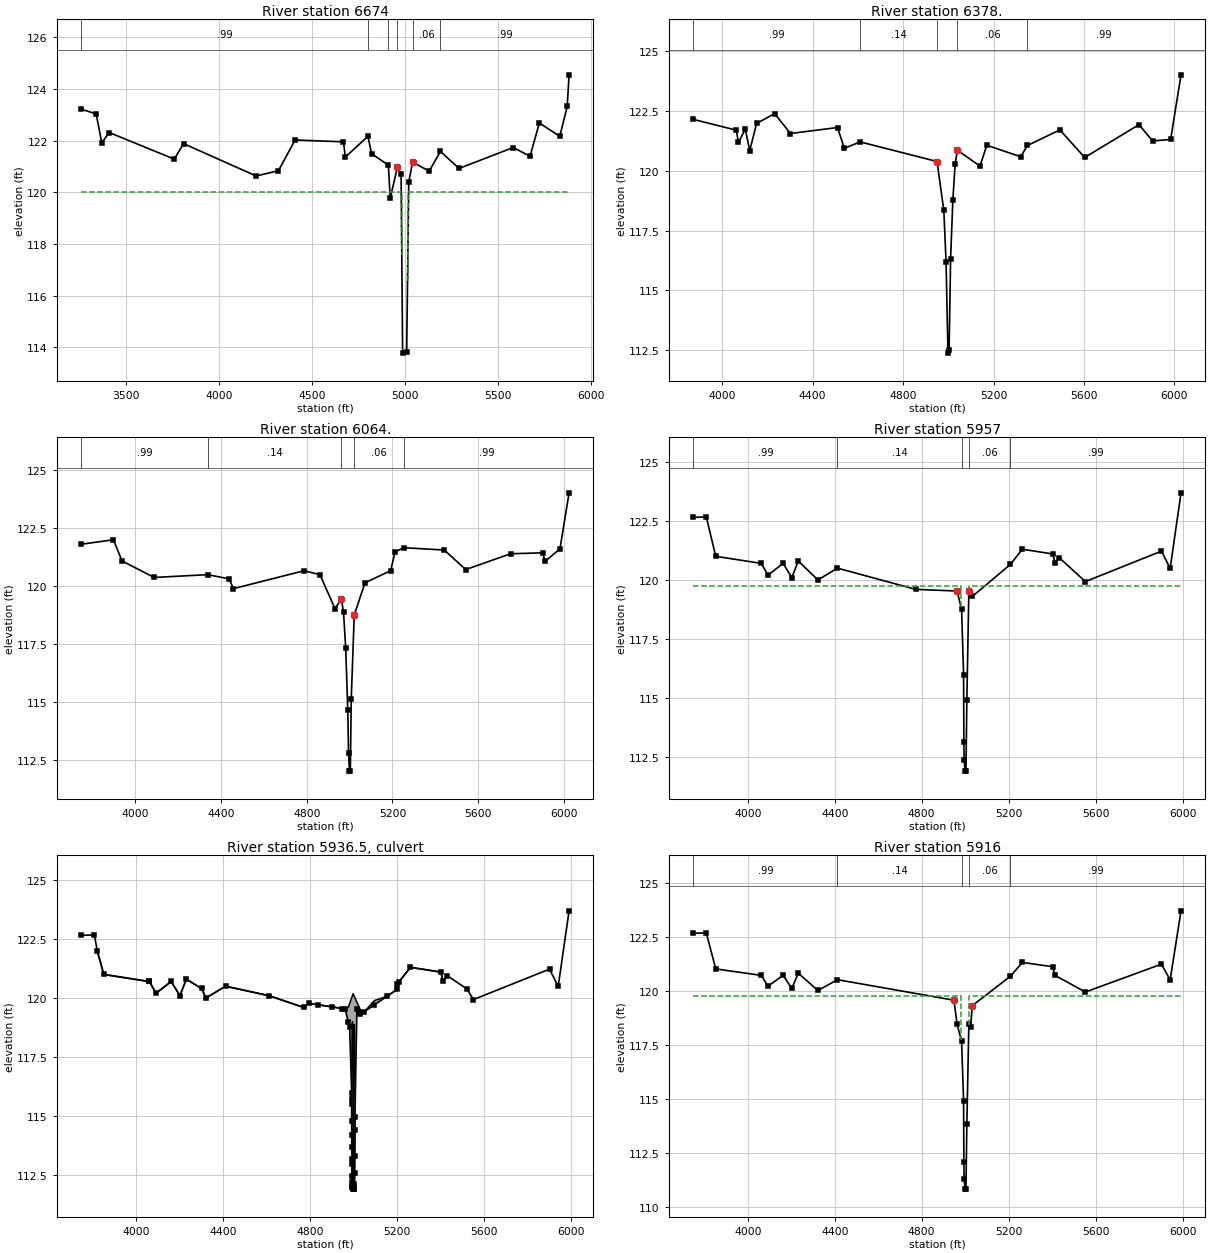
Type RM Length L Ch R = 1 ,6674    ,287,275,265
BEGIN DESCRIPTION:
SPRING CYPRESS RD - XS 2 - Adjust Reach Lengths by -21'
Downstream Section of Bridge/Culvert/Weir
END DESCRIPTION:
XS GIS Cut Line= 4
      3098107.84      13956726.9      3096760.99     13956076.61
      3096176.19     13955782.49      3095757.04      13955605.5
#Sta/Elev= 30
  3260.3  123.21  3340.3  123.03  3370.3  121.91  3410.3  122.31  3760.3  121.28
  3810.3  121.88  4200.3  120.63  4320.3  120.83  4410.3  122.02  4670.3  121.95
  4680.3  121.36  4801.8  122.16  4821.8  121.49  4911.8  121.05  4921.8  119.77
  4960.2  120.96  4980.2  120.71  4988.6  113.78  5010.4  113.84  5021.4  120.39
  5041.8  121.16  5131.8  120.82  5191.8  121.58  5291.8  120.92  5583.8  121.73
  5673.8  121.39  5723.8  122.68  5833.8  122.16  5873.8  123.32  5883.8  124.54
#Mann= 6 ,-1 , 0
  3260.3     .99       0  4801.8     .06       0  4911.8    .045       0
  4960.2    .013       0  5041.8     .06       0  5191.8     .99       0
#XS Ineff= 2 , 0
       0    4984     120    5015       0     120
Permanent Ineff=
       F       F
Bank Sta=4960.2,5041.8
XS Rating Curve= 0
Exp/Cntr=.5,.3

Type RM Length L Ch R = 1 ,6378.   ,378,314,260
BEGIN DESCRIPTION:
SPRING CYPRESS RD - XS 1
Interpolated channel - LIDAR overbanks
END DESCRIPTION:
XS GIS Cut Line= 4
  3097749.950957  13956248.50305      3097284.98     13956019.86
      3096312.29      13955521.3     3095788.203    13955367.506
#Sta/Elev= 30
    3872  122.14    4062  121.69    4072  121.18    4102  121.73    4122  120.84
    4152  121.97    4232  122.38    4302  121.55  4510.1   121.8  4540.1  120.93
  4610.1   121.2  4950.1  120.38  4980.1  118.34  4990.1  116.17 4998.37  112.38
 5003.43   112.5  5010.1  116.33  5020.1  118.79  5030.1  120.28  5040.1  120.85
  5140.1  120.19  5170.1  121.06  5320.1  120.58  5350.1  121.05  5493.2   121.7
  5603.2  120.55  5843.2  121.92  5903.2  121.24  5983.2   121.3  6029.1     124
#Mann= 5 ,-1 , 0
    3872     .99       0  4610.1     .14       0  4950.1     .04       0
  5040.1     .06       0  5350.1     .99       0
Bank Sta=4950.1,5040.1
XS Rating Curve= 0
Exp/Cntr=.3,.1

Type RM Length L Ch R = 1 ,6064.   ,111.3,107,103.6
BEGIN DESCRIPTION:
CULVERT 690' DS OF SPRING CYPRESS - XS 4
Interpolated channel - LIDAR overbanks
END DESCRIPTION:
XS GIS Cut Line= 4
      3097900.22    13955982.093      3097017.54    13955425.004
      3096608.17     13955452.09     3095794.247    13955333.742
#Sta/Elev= 30
  3747.9  121.79  3897.9  121.98  3937.9  121.07  4087.9  120.36  4337.9  120.48
  4437.9   120.3  4457.9  119.88  4787.9  120.65  4861.7  120.48  4931.7  119.02
  4961.7  119.42  4971.7  118.87  4981.7  117.34  4991.7  114.64 4994.99  112.81
 4999.51  112.03 5003.52  112.05 5007.85  115.15  5021.7  118.74  5071.7  120.13
  5191.7  120.65  5211.9  121.45  5251.9  121.64  5441.9  121.54  5541.9   120.7
  5751.9  121.38  5901.9  121.42  5911.9  121.05  5981.9  121.59  6024.4     124
#Mann= 5 ,-1 , 0
  3747.9     .99       0  4337.9     .14       0  4961.7     .04       0
  5021.7     .06       0  5251.9     .99       0
Bank Sta=4961.7,5021.7
XS Rating Curve= 0
Exp/Cntr=.5,.3

Type RM Length L Ch R = 1 ,5957    ,41,41,41
BEGIN DESCRIPTION:
CULVERT 690' DS OF SPRING CYPRESS - XS 3
Upstream Section of Bridge/Culvert/Weir
END DESCRIPTION:
XS GIS Cut Line= 4
       3097885.8       13955875.      3097003.21      13955318.9
      3096593.83     13955345.99      3095812.15      13955232.1
#Sta/Elev= 30
  3749.1  122.66  3809.1  122.68  3852.5  121.01  4062.5  120.71  4092.5  120.21
  4162.5  120.71  4202.5  120.11  4232.5  120.81  4322.5  120.01  4412.5  120.51
  4772.5  119.61  4962.8  119.54  4983.7  118.76  4992.8  115.99    4994  113.15
  4995.3   112.4  4999.9  111.91  5003.7  111.93  5007.8  114.93    5017  119.55
    5033  119.31  5208.4  120.67  5263.3  121.31  5403.3  121.11  5413.3  120.71
  5433.1  120.95  5553.1  119.94  5903.1  121.23  5943.1   120.5  5993.1   123.7
#Mann= 5 ,-1 , 0
  3749.1     .99       0  4412.5     .14       0  4983.7     .04       0
    5017     .06       0  5208.4     .99       0
#XS Ineff= 2 , 0
       0    4982  119.74    5018       0  119.74
Permanent Ineff=
       F       T
Bank Sta=4962.8,5017
XS Rating Curve= 0
Exp/Cntr=.5,.3

Type RM Length L Ch R = 2 ,5936.5  ,,,
BEGIN DESCRIPTION:
CULVERT 690' DS OF SPRING CYPRESS.
Structure ID: K120-03-00-S4
END DESCRIPTION:
Bridge Culvert--1,0,-1,-1, 0
Deck Dist Width WeirC Skew NumUp NumDn MinLoCord MaxHiCord MaxSubmerge Is_Ogee
10,24.5,2.6,0, 40, 40, , , .95, 0, ,,,
  3822.5  3852.5  4060.3  4062.5  4092.5  4162.5  4202.5  4232.5  4302.5  4322.5
  4412.5  4612.5  4772.5  4795.3  4838.4  4903.4  4948.7  4962.8  4977.6  4983.7
  4992.8    4994  4995.3  4999.6  4999.9  5003.7    5006  5007.8    5017  5024.8
    5033  5050.6  5097.9  5155.8  5202.7  5203.3  5208.4  5263.3  5403.3  5413.3
     122     121   120.7   120.7   120.2   120.7   120.1   120.8   120.4     120
   120.5   120.1   119.6  119.77  119.72  119.63  119.57  119.59  119.62  119.78
  120.01  120.04  120.08  120.19  120.18  120.11  120.06  120.02  119.83  119.67
   119.5  119.42   119.9  120.08  120.37   120.6  120.66   121.3   121.1   120.7
     122     121   120.7   120.7   120.2   120.7   120.1   120.8   120.4     120
   120.5   120.1   119.6  119.77  119.71  119.62  119.55  119.53  118.98  118.75
  115.98  113.14  112.39  111.93   111.9  111.92  113.41  114.92  119.54  119.42
   119.3  119.41  119.71  120.07  120.37   120.6  120.66   121.3   121.1   120.7
  3822.5  3852.5  4060.3  4062.5  4092.5  4162.5  4202.5  4232.5  4302.5  4322.5
  4412.5  4612.5  4772.5  4795.3  4838.4  4903.4  4948.7  4962.8  4977.6  4983.7
  4992.8    4994  4995.3  4999.6  4999.9  5003.7    5006  5007.8    5017  5024.8
    5033  5050.6  5097.9  5155.8  5202.7  5203.3  5208.4  5263.3  5403.3  5413.3
     122     121   120.7   120.7   120.2   120.7   120.1   120.8   120.4     120
   120.5   120.1   119.6  119.77  119.72  119.63  119.57  119.59  119.62  119.78
  120.01  120.04  120.08  120.19  120.18  120.11  120.06  120.02  119.83  119.67
   119.5  119.42   119.9  120.08  120.37   120.6  120.66   121.3   121.1   120.7
  120.91  119.91  119.61  119.61  119.11  119.61  119.01  119.71  119.31  118.91
  119.41  119.01  118.51  118.68  118.62  118.53  118.46  118.44  117.89  117.66
  114.89  112.05   111.3  110.84  110.81  110.83  112.32  113.83  118.45  118.33
  118.21  118.32  118.62  118.98  119.28  119.51  119.57  120.21  120.01  119.61
BR Coef= 1 , 1 , 0 ,1.25, 0 ,,,.8,-1,2,0,
WSPro=,,,, 1 ,,,, 0 ,,,, 0 ,,,,-1 ,-1 ,-1 , 0 , 0 , 0 , 0 , 0
Culvert=1,7,,24.5,.015,.5,1,1,3,112.01,4996.4,110.89,4996.4,Culvert #1  , 0 ,10
Culvert Bottom n=.015
Culvert=1,7,,24.5,.015,.5,1,1,3,111.91,5004.4,111.45,5004.4,Culvert #2  , 0 ,10
Culvert Bottom n=.015
BR U #Sta/Elev= 63
  3749.1  122.66  3809.1  122.68  3822.5  122.01  3852.5  121.01  4060.3  120.71
  4062.5  120.71  4092.5  120.21  4162.5  120.71  4202.5  120.11  4232.5  120.81
  4302.5  120.41  4322.5  120.01  4412.5  120.51  4612.5  120.11  4772.5  119.61
  4795.3  119.78  4838.4  119.72  4903.4  119.63  4948.7  119.56  4962.8  119.54
  4977.6  118.99  4983.7  118.76  4992.8  115.99  4992.9  115.72  4992.9  115.51
 4992.98   114.8 4993.15  114.19 4993.41  113.68 4993.79  113.19 4993.99  112.97
 4994.67  112.45 4995.28   112.2 4996.18     112 4996.64     112 4997.43  112.14
  4999.6  111.94  4999.9  111.91  5003.7  111.93 5003.72  111.97 5004.63  111.92
 5005.68  112.14 5006.48  112.61  5007.2   113.3 5007.76   114.4 5007.87  114.97
    5017  119.55  5024.8  119.43    5033  119.31  5050.6  119.42  5097.9  119.72
  5155.8  120.08  5202.7  120.38  5203.3  120.61  5208.4  120.67  5263.3  121.31
  5403.3  121.11  5413.3  120.71  5433.1  120.95  5523.1  120.39  5553.1  119.94
  5903.1  121.23  5943.1   120.5  5993.1   123.7
BR U #Mann= 5
  3749.1     .99  4412.5     .14  4983.7     .04    5017     .06  5208.4     .99
BR D #Sta/Elev= 60
  3749.1  122.66  3809.1  122.68  3822.5  122.01  3852.5  121.01  4060.3  120.71
  4062.5  120.71  4092.5  120.21  4162.5  120.71  4202.5  120.11  4232.5  120.81
  4302.5  120.41  4322.5  120.01  4412.5  120.51  4612.5  120.11  4772.5  119.61
  4795.3  119.78  4838.4  119.72  4903.4  119.63  4948.7  119.56  4962.8  118.44
  4977.6  117.89  4983.7  117.66  4992.8  114.89 4992.91  114.64 4992.91  114.29
 4993.14   113.1 4993.59  112.26 4994.79  111.28 4995.84  110.96 4996.61   110.9
 4997.47  111.04  4999.6  110.84  4999.9  110.81  5003.7  110.83 5004.69  111.46
 5005.34  111.59 5006.17  111.91 5006.71  112.32 5007.17   112.8 5007.58   113.5
 5007.66   113.7  5007.8  113.83    5017  118.45  5024.8  118.33    5033  119.31
  5050.6  119.42  5097.9  119.72  5155.8  120.08  5202.7  120.38  5203.3  120.61
  5208.4  120.67  5263.3  121.31  5403.3  121.11  5413.3  120.71  5433.1  120.95
  5523.1  120.39  5553.1  119.94  5903.1  121.23  5943.1   120.5  5993.1   123.7
BR D #Mann= 5
  3749.1     .99  4412.5     .14  4983.7     .04    5017     .06  5208.4     .99
BC Design=,, 0 ,, 0 ,,,,,,
BC HTab HWMax=122.01

Type RM Length L Ch R = 1 ,5916    ,126,126,127
BEGIN DESCRIPTION:
CULVERT 690' DS OF SPRING CYPRESS - XS 2
Downstream Section of Bridge/Culvert/Weir
END DESCRIPTION:
XS GIS Cut Line= 4
        3097899.      13955845.5      3097007.09     13955275.64
      3096593.54       13955303. 3095808.7833295 13955194.935147
#Sta/Elev= 30
  3749.1  122.66  3809.1  122.68  3852.5  121.01  4062.5  120.71  4092.5  120.21
  4162.5  120.71  4202.5  120.11  4232.5  120.81  4322.5  120.01  4412.5  120.51
  4948.7  119.56  4962.8  118.44  4983.7  117.66  4992.8  114.89    4994  112.05
  4995.3   111.3  4999.9  110.81  5003.7  110.83  5007.8  113.83    5017  118.45
  5024.8  118.33    5033  119.31  5208.4  120.67  5263.3  121.31  5403.3  121.11
  5413.3  120.71  5553.1  119.94  5903.1  121.23  5943.1   120.5  5993.1   123.7
#Mann= 5 ,-1 , 0
  3749.1     .99       0  4412.5     .14       0  4983.7     .04       0
    5017     .06       0  5208.4     .99       0
#XS Ineff= 2 , 0
       0    4982  119.74    5018       0  119.74
Permanent Ineff=
       F       T
Bank Sta=4948.7,5033
XS Rating Curve= 0
Exp/Cntr=.5,.3

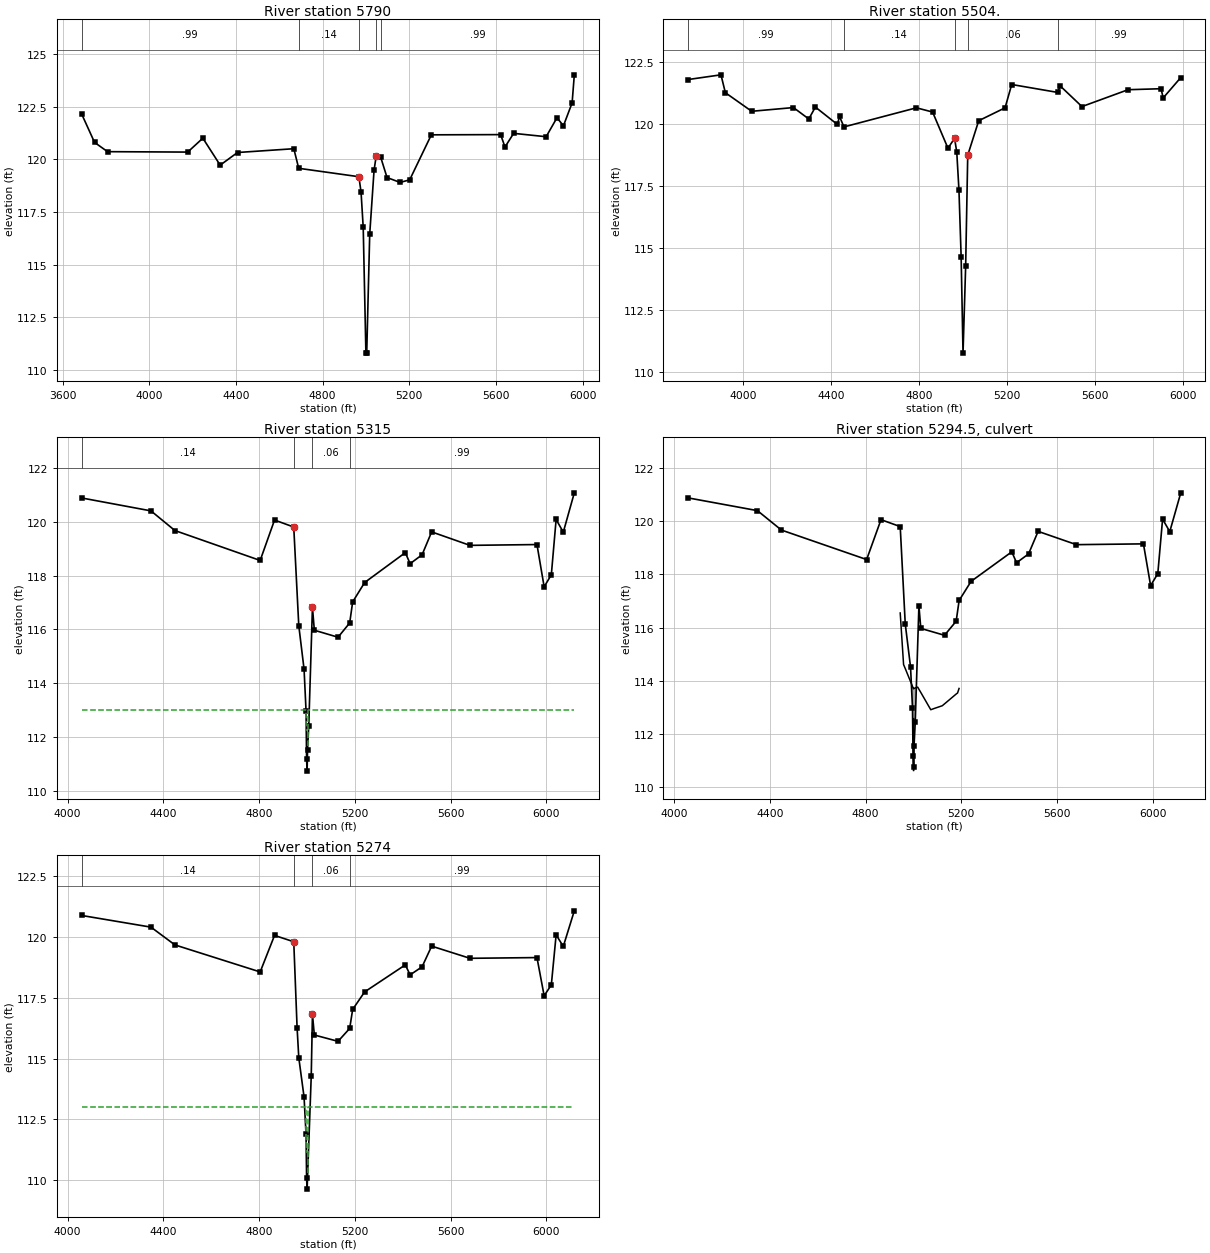
Type RM Length L Ch R = 1 ,5790    ,267,286,301
BEGIN DESCRIPTION:
CULVERT 690' DS OF SPRING CYPRESS - XS 1
Interpolated XS
XS 125 FT D/S CULVERT 2
END DESCRIPTION:
XS GIS Cut Line= 4
        3097882.       13955805.      3097022.72     13955150.64
      3096609.16       13955178.      3095836.97     13955067.51
#Sta/Elev= 30
  3687.1  122.17  3747.1  120.81  3807.1  120.37  4177.1  120.35  4247.1  121.01
  4327.1  119.73  4407.1  120.33  4667.1  120.51  4689.6  119.58  4967.5  119.18
  4977.5  118.45  4987.5  116.77  4999.9   110.8  5003.7  110.82  5017.5  116.45
  5037.5  119.48  5047.5  120.17  5067.5  120.13  5097.5  119.14  5157.5  118.91
    5202  119.03    5302  121.17    5622  121.18    5642  120.59    5682  121.24
    5832  121.08    5882  121.98    5912   121.6    5952  122.69  5962.1  124.02
#Mann= 5 ,-1 , 0
  3687.1     .99       0  4689.6     .14       0  4967.5    .055       0
  5047.5     .06       0  5067.5     .99       0
Bank Sta=4967.5,5047.5
XS Rating Curve= 0
Exp/Cntr=.3,.1

Type RM Length L Ch R = 1 ,5504.   ,162,189,214
BEGIN DESCRIPTION:
CULVERT NORTH OF WALKWAY BRIDGE - XS 4
Interpolated channel - LIDAR overbanks
END DESCRIPTION:
XS GIS Cut Line= 4
     3097868.886    13955596.479      3097006.58     13954929.93
      3096654.44     13954841.88      3095877.27     13954690.36
#Sta/Elev= 30
  3747.9  121.79  3897.9  121.98  3917.9  121.26  4037.9  120.51  4227.9  120.66
  4297.9   120.2  4327.9  120.68  4427.9  119.98  4437.9   120.3  4457.9  119.88
  4787.9  120.65  4861.7  120.48  4931.7  119.02  4961.7  119.42  4971.7  118.87
  4981.7  117.34  4991.7  114.64 5000.26  110.76 5012.23  114.26  5021.7  118.74
  5071.7  120.13  5191.7  120.65  5221.9  121.59  5431.9  121.27  5441.9  121.54
  5541.9   120.7  5751.9  121.38  5901.9  121.42  5911.9  121.05  5991.9  121.87
#Mann= 5 ,-1 , 0
  3747.9     .99       0  4457.9     .14       0  4961.7    .055       0
  5021.7     .06       0  5431.9     .99       0
Bank Sta=4961.7,5021.7
XS Rating Curve= 0
Exp/Cntr=.5,.3

Type RM Length L Ch R = 1 ,5315    ,41,41,41
BEGIN DESCRIPTION:
CULVERT NORTH OF WALKWAY BRIDGE - XS 3
Upstream Section of Bridge/Culvert/Weir
END DESCRIPTION:
XS GIS Cut Line= 4
       3097645.9      13955294.7      3097063.93      13954843.9
      3096751.82      13954599.5      3095956.32     13954125.53
#Sta/Elev= 30
  4058.2  120.88  4348.2   120.4  4448.2  119.67  4804.4  118.56  4864.4  120.06
  4944.7   119.8  4965.7  116.14  4987.8  114.52    4996  112.99  4998.4  111.18
  5000.5  110.74  5002.3  111.54  5007.4  112.43  5022.8  116.82  5030.7  115.97
  5129.7  115.71  5178.4  116.24  5190.8  117.02  5240.8  117.74  5410.8  118.85
  5430.8  118.44  5480.8  118.77  5520.8  119.62  5680.8  119.12  5960.8  119.15
  5990.8  117.58  6020.8  118.03  6040.8  120.08  6070.8  119.61  6116.8  121.07
#Mann= 4 ,-1 , 0
  4058.2     .14       0  4944.7    .055       0  5022.8     .06       0
  5178.4     .99       0
#XS Ineff= 2 , 0
       0    4997     113    5003       0     113
Permanent Ineff=
       F       F
#Block Obstruct= 2 , 0
       0                    5960       0   119.1
Bank Sta=4944.7,5022.8
XS Rating Curve= 0
Exp/Cntr=.5,.3

Type RM Length L Ch R = 2 ,5294.5  ,,,
BEGIN DESCRIPTION:
CULVERT NORTH OF WALKWAY BRIDGE
Structure ID: K120-03-00-S3
END DESCRIPTION:
Bridge Culvert--1,0,-1,-1, 0
Deck Dist Width WeirC Skew NumUp NumDn MinLoCord MaxHiCord MaxSubmerge Is_Ogee
10,22,3,0, 23, 23, , , .95, 0, 0,0,,
  4944.7  4958.7  4965.7  4974.7  4987.8    4996  4997.6  4998.4    5000  5000.5
  5001.5  5002.3  5007.4  5017.7  5022.8  5030.7  5072.3  5087.7  5120.4  5129.7
  5178.4  5184.3  5190.5
  116.55  114.61  114.46  114.26  113.97  113.79  113.75  113.74   113.7   113.7
  113.71  113.71  113.73  113.76  113.68  113.56  112.91  112.96  113.06  113.13
   113.5  113.54  113.71
                                                                                
                                                                                
                        
  4944.7  4958.7  4965.7  4974.7  4987.8    4996  4997.6  4998.4    5000  5000.5
  5001.5  5002.3  5007.4  5017.7  5022.8  5030.7  5072.3  5087.7  5120.4  5129.7
  5178.4  5184.3  5190.5
  116.55  114.61  114.46  114.26  113.97  113.79  113.75  113.74   113.7   113.7
  113.71  113.71  113.73  113.76  113.68  113.56  112.91  112.96  113.06  113.13
   113.5  113.54  113.71
                                                                                
                                                                                
                        
BR Coef= 1 , 1 , 0 ,1.25, 0 ,,,.8,0,2,0,
WSPro=,,,, 1 ,,,, 0 ,,,, 0 ,,,,-1 ,-1 ,-1 , 0 , 0 , 0 , 0 , 0
Culvert=1,2,,22,.024,.9,1,2,3,110.6,5000.4,110.47,5000.4,Culvert #1  , 0 ,10
Culvert Bottom n=.024
BC Design=,, 0 ,, 0 ,,,,,,
BC HTab HWMax=120.5

Type RM Length L Ch R = 1 ,5274    ,237,228,216
BEGIN DESCRIPTION:
CULVERT NORTH OF WALKWAY BRIDGE - XS 2
Downstream Section of Bridge/Culvert/Weir
END DESCRIPTION:
XS GIS Cut Line= 4
       3097659.4       13955264.      3097091.52     13954813.51
      3096773.99     13954564.86      3095979.97     13954095.12
#Sta/Elev= 30
  4058.2  120.88  4348.2   120.4  4448.2  119.67  4804.4  118.56  4864.4  120.06
  4944.7   119.8  4958.7  116.26  4965.7  115.04  4987.8  113.42    4996  111.89
  4998.4  110.08  5000.5  109.64  5017.7  114.27  5022.8  116.82  5030.7  115.97
  5129.7  115.71  5178.4  116.24  5190.8  117.02  5240.8  117.74  5410.8  118.85
  5430.8  118.44  5480.8  118.77  5520.8  119.62  5680.8  119.12  5960.8  119.15
  5990.8  117.58  6020.8  118.03  6040.8  120.08  6070.8  119.61  6116.8  121.07
#Mann= 4 ,-1 , 0
  4058.2     .14       0  4944.7    .055       0  5022.8     .06       0
  5178.4     .99       0
#XS Ineff= 2 , 0
       0    4997     113    5003       0     113
Permanent Ineff=
       F       F
#Block Obstruct= 2 , 0
       0                    5960       0  119.15
Bank Sta=4944.7,5022.8
XS Rating Curve= 0
Exp/Cntr=.5,.3