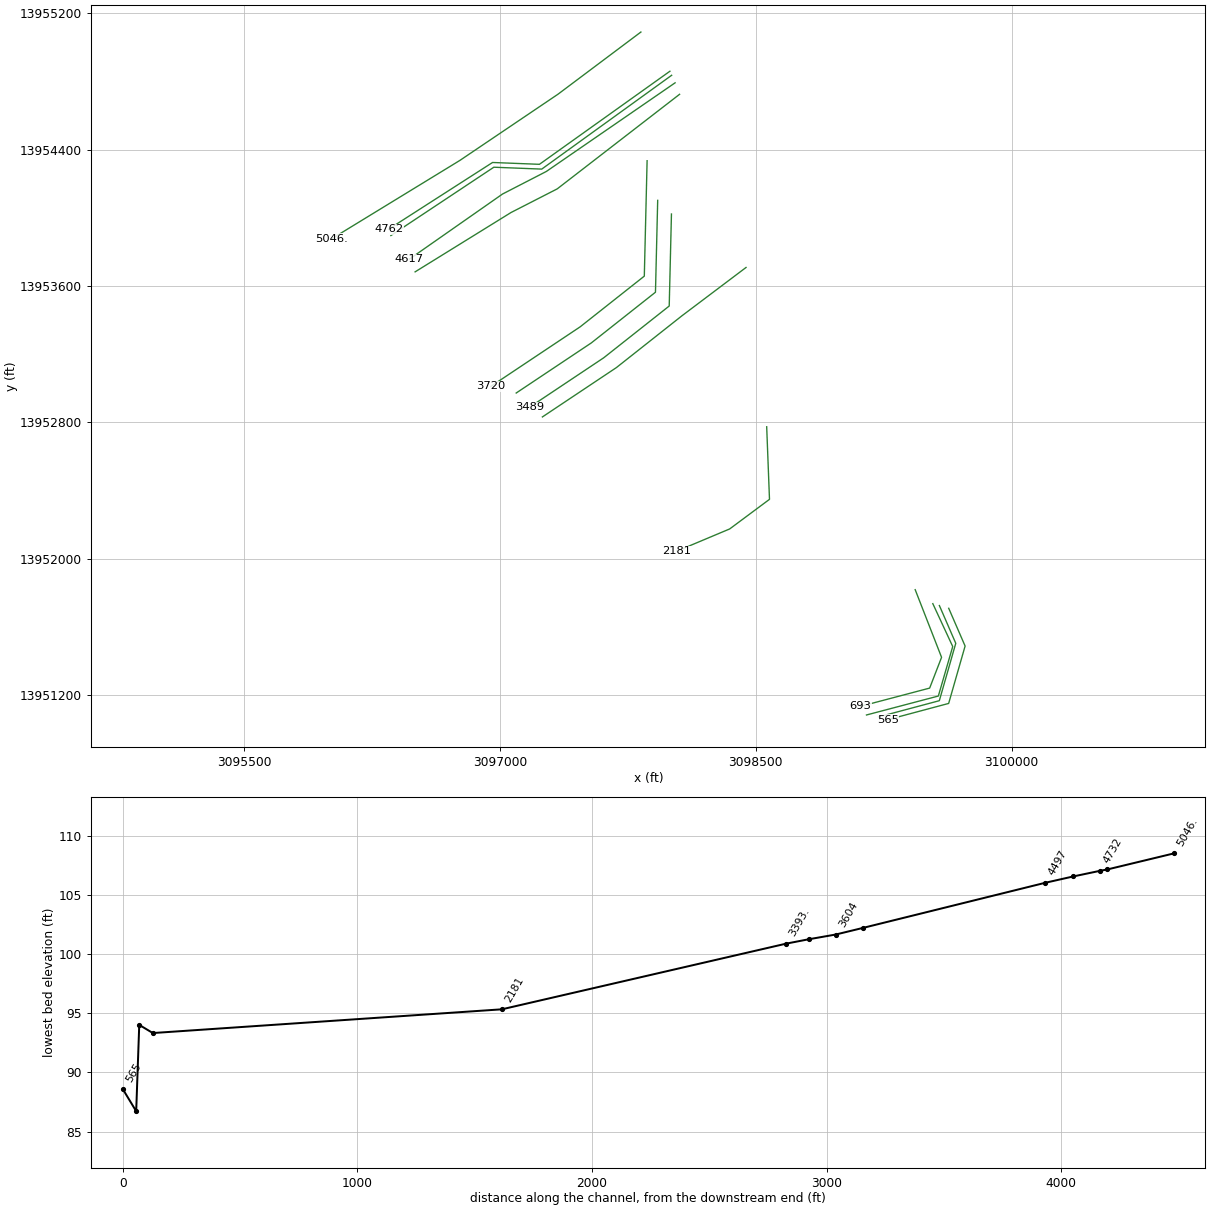
HEC-RAS study K120-03-00.prj: K120-03-00

--- K120-03-00.g01 (geometry) --- (continued)

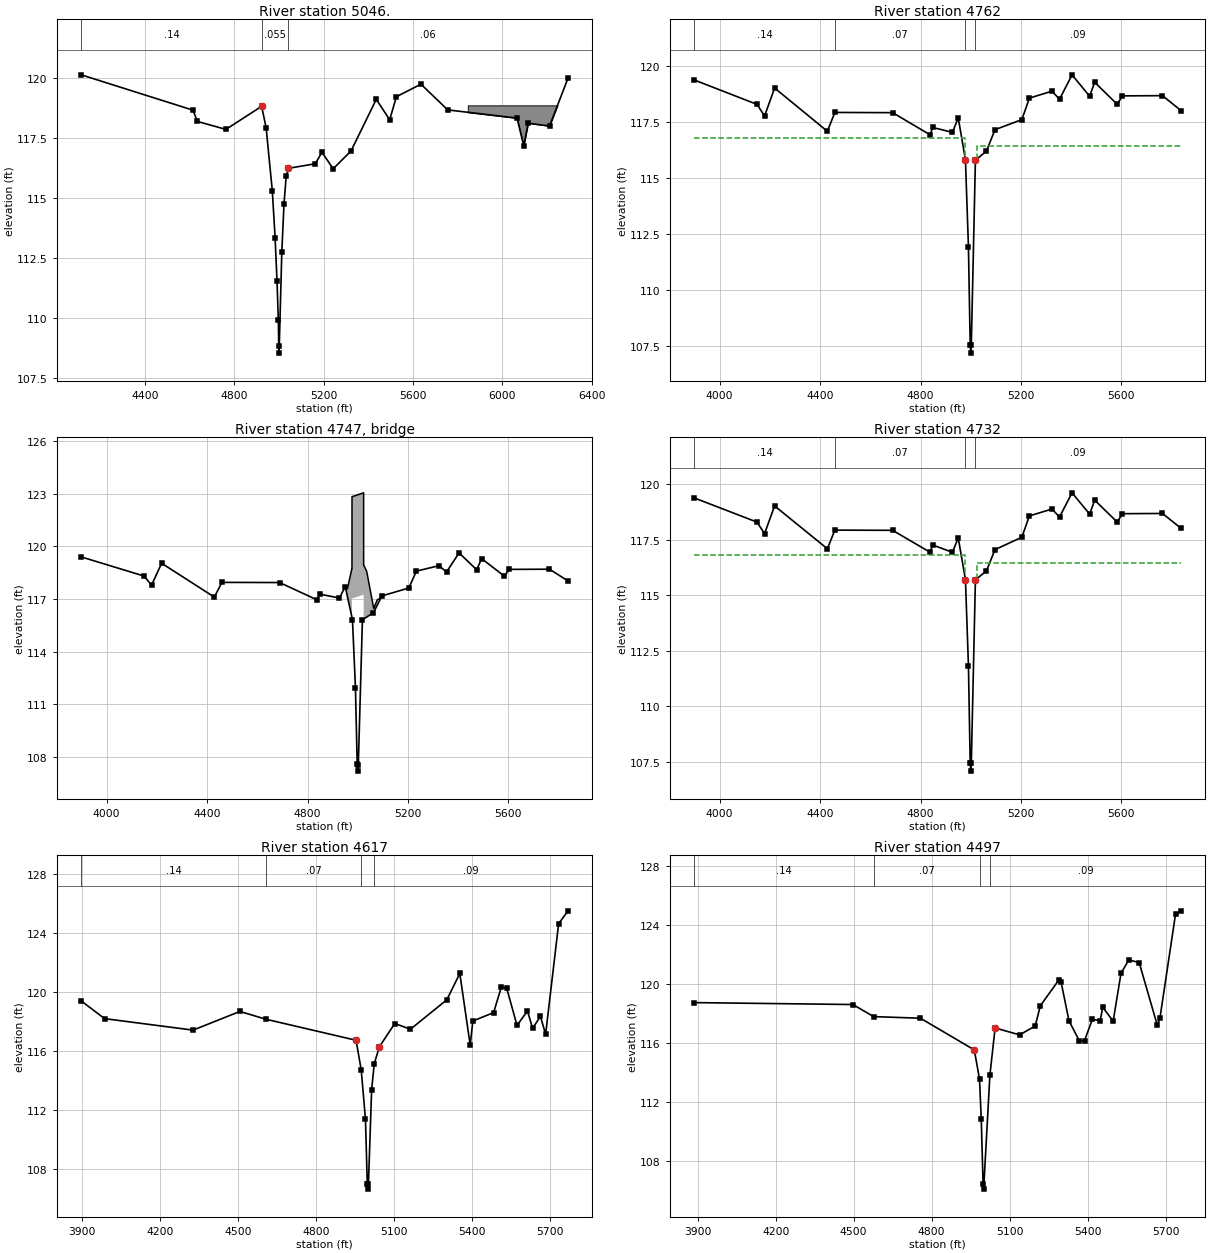
Type RM Length L Ch R = 1 ,5046.   ,306,284,194
BEGIN DESCRIPTION:
CULVERT NORTH OF WALKWAY BRIDGE - XS 1
CONCRETE FOOT BRIDGE 1150' US LOUETTA - XS 4
Interpolated channel - LIDAR overbanks
END DESCRIPTION:
XS GIS Cut Line= 4
       3097827.3     13955088.71      3097341.19     13954724.12
      3096766.63     13954336.39     3096014.148    13953876.393
#Sta/Elev= 30
  4114.7  120.13  4614.7  118.66  4634.7  118.19  4762.3  117.86  4922.3  118.82
  4942.3  117.93 4970.05   115.3 4982.68  113.33 4991.09  111.54 4997.02  109.91
 4998.76  108.85 5000.28  108.55 5012.49  112.74  5022.3  114.76  5032.3  115.92
  5042.3  116.24  5162.3  116.43  5192.3  116.91  5242.3  116.22  5322.3  116.96
  5435.5  119.11  5495.5  118.26  5525.5  119.22  5635.5  119.74  5755.5  118.67
  6065.5  118.33  6095.5  117.18  6115.5  118.12  6211.1     118  6294.1     120
#Mann= 3 ,-1 , 0
  4114.7     .14       0  4922.3    .055       0  5042.3     .06       0
#Block Obstruct= 1 ,-1
 5845.07  6321.6  118.86
Bank Sta=4922.3,5042.3
XS Rating Curve= 0
Exp/Cntr=.5,.3

Type RM Length L Ch R = 1 ,4762    ,30,30,30
BEGIN DESCRIPTION:
CONCRETE FOOT BRIDGE 1150' US LOUETTA - XS 3
Upstream Section of Bridge/Culvert/Weir
END DESCRIPTION:
XS GIS Cut Line= 4
       3097997.3      13954858.8      3097232.53     13954313.21
      3096957.67     13954323.98      3096348.31     13953932.91
#Sta/Elev= 30
  3898.9  119.39  4148.9   118.3  4178.9  117.78  4218.9  119.03  4428.9   117.1
  4458.9  117.94  4688.9  117.93  4838.4  116.94  4848.4  117.27    4927  117.05
  4950.2   117.7  4978.9  115.82  4990.8  111.94  4997.8  107.57    5000  107.19
  5002.2  107.54  5018.6  115.81  5062.4  116.21  5096.5  117.17  5203.5  117.62
  5233.5  118.58  5323.5  118.89  5353.5  118.53  5403.5  119.62  5473.5  118.66
  5493.5  119.29  5583.5   118.3  5603.5  118.68  5763.5  118.69  5837.6  118.02
#Mann= 4 ,-1 , 0
  3898.9     .14       0  4458.9     .07       0  4978.9    .055       0
  5018.6     .09       0
#XS Ineff= 2 , 0
       0    4976   116.8  5024.5       0  116.46
Permanent Ineff=
       F       F
Bank Sta=4978.9,5018.6
XS Rating Curve= 0
Exp/Cntr=.5,.3

Type RM Length L Ch R = 3 ,4747    ,,,
BEGIN DESCRIPTION:
CONCRETE FOOT BRIDGE 1150' US LOUETTA
Structure ID: K120-03-00-S1A
END DESCRIPTION:
Bridge Culvert--1,0,-1,-1, 0
Deck Dist Width WeirC Skew NumUp NumDn MinLoCord MaxHiCord MaxSubmerge Is_Ogee
10,7.4,2.6,0, 30, 30, , , .95, 0, ,,,
  4950.2  4959.2  4976.6 4976.71  4976.8  4976.9 4976.99  4977.1 4977.21  4978.9
  4990.8  4997.8  4998.3    5000  5001.1  5002.2    5011  5018.6  5023.2 5023.26
 5023.37 5023.48 5023.59  5023.7  5035.8  5062.4  5063.5  5077.9  5083.7  5096.5
  117.66   117.6  118.72  118.72  118.72  118.72  118.72  122.82  122.82  122.83
  122.88  122.92  122.92  122.93  122.93  122.94  122.98  123.02  123.04  123.04
  123.04  118.94  118.94  118.93  118.56  116.54  116.46  116.95  116.99  117.13
  117.65  117.06  115.92  115.91  117.02  117.02  117.02  117.02  117.02  117.03
  117.08  117.12  117.12  117.13  117.13  117.14  117.18  117.22  117.24  117.24
  117.24  117.24  117.24  115.81  115.92  116.16   116.2  116.76  116.98  117.12
  4950.2  4959.2  4976.6 4976.71  4976.8  4976.9 4976.99  4977.1 4977.21  4978.9
  4990.8  4997.8  4998.3    5000  5001.1  5002.2    5011  5018.6  5023.2 5023.26
 5023.37 5023.48 5023.59  5023.7  5035.8  5062.4  5063.5  5077.9  5083.7  5096.5
  117.66   117.6  118.72  118.72  118.72  118.72  118.72  122.82  122.82  122.83
  122.88  122.92  122.92  122.93  122.93  122.94  122.98  123.02  123.04  123.04
  123.04  118.94  118.94  118.93  118.56  116.54  116.46  116.95  116.99  117.13
     117     117     115  115.91  117.02  117.02  117.02  117.02  117.02  117.03
  117.08  117.12  117.12  117.13  117.13  117.14  117.18  117.22  117.24  117.24
     117     117     117     115     115     116     116     116     116     117
BR Coef= 1 , 1 , 0 ,1.25, 0 ,,,.8,0,2,0,
WSPro=,,,, 1 ,,,, 0 ,,,, 0 ,,,,-1 ,-1 ,-1 , 0 , 0 , 0 , 0 , 0
BC Design=,, 0 ,, 0 ,,,,,,
BC HTab HWMax=120.15

Type RM Length L Ch R = 1 ,4732    ,115,115,114
BEGIN DESCRIPTION:
CONCRETE FOOT BRIDGE 1150' US LOUETTA - XS 2
Downstream Section of Bridge/Culvert/Weir
END DESCRIPTION:
XS GIS Cut Line= 4
       3098007.5      13954835.1      3097246.08     13954285.18
      3096965.14      13954296.2      3096361.83     13953895.74
#Sta/Elev= 30
  3898.9  119.39  4148.9   118.3  4178.9  117.78  4218.9  119.03  4428.9   117.1
  4458.9  117.94  4688.9  117.93  4838.4  116.94  4848.4  117.27    4927  116.94
  4950.2  117.59  4978.9  115.71  4990.8  111.83  4997.8  107.46    5000  107.08
  5002.2  107.43  5018.6   115.7  5062.4   116.1  5096.5  117.06  5203.5  117.62
  5233.5  118.58  5323.5  118.89  5353.5  118.53  5403.5  119.62  5473.5  118.66
  5493.5  119.29  5583.5   118.3  5603.5  118.68  5763.5  118.69  5837.6  118.02
#Mann= 4 ,-1 , 0
  3898.9     .14       0  4458.9     .07       0  4978.9    .055       0
  5018.6     .09       0
#XS Ineff= 2 , 0
       0    4976   116.8  5024.5       0  116.46
Permanent Ineff=
       F       F
Bank Sta=4978.9,5018.6
XS Rating Curve= 0
Exp/Cntr=.5,.3

Type RM Length L Ch R = 1 ,4617    ,121,120,120
BEGIN DESCRIPTION:
CONCRETE FOOT BRIDGE 1150' US LOUETTA - XS 1
Interpolated XS
XS 100 FT D/S OF CONCRETE FOOTBRIDGE
END DESCRIPTION:
XS GIS Cut Line= 4
       3098027.8       13954791.       3097272.9     13954271.31
      3097016.01     13954138.96      3096469.96     13953757.19
#Sta/Elev= 30
    3898  119.39    3988  118.19    4328  117.41    4508  118.68    4608  118.15
  4954.6  116.72  4974.6   114.7  4990.8  111.35  4997.8  106.98    5000   106.6
  5002.2  106.95  5014.6  113.37  5024.6  115.13  5044.6  116.29  5103.6  117.86
  5163.6  117.47  5303.6  119.47  5353.6  121.26  5393.6  116.38  5403.6  118.03
  5483.6   118.6  5513.6  120.36  5533.6  120.28  5573.6  117.73  5613.6  118.71
  5633.6  117.54  5663.6  118.34  5683.6  117.13  5733.6  124.65  5769.9  125.52
#Mann= 4 ,-1 , 0
    3898     .14       0    4608     .07       0  4974.6    .055       0
  5024.6     .09       0
Bank Sta=4954.6,5044.6
XS Rating Curve= 0
Exp/Cntr=.3,.1

Type RM Length L Ch R = 1 ,4497    ,776,777,777
BEGIN DESCRIPTION:
Interpolated XS
XS 200 FT D/S OF CONCRETE FOOTBRIDGE
END DESCRIPTION:
XS GIS Cut Line= 4
        3098054.      13954723.6      3097336.74     13954169.22
       3097066.1     13954030.73      3096503.76     13953682.85
#Sta/Elev= 30
  3886.9  118.72  4496.9  118.59  4576.9  117.77  4756.9  117.66  4964.1  115.51
  4984.1  113.53  4990.8  110.81  4997.8  106.44    5000  106.06  5024.1   113.8
  5044.1     117  5138.2  116.53  5198.2  117.13  5218.2  118.51  5288.2  120.23
  5298.2  120.09  5328.2  117.49  5368.2  116.12  5388.2  116.14  5418.2  117.59
  5448.2  117.49  5458.2   118.4  5498.2  117.46  5528.2   120.7  5558.2  121.62
  5598.2  121.44  5668.2  117.17  5678.2  117.68  5738.2  124.74  5759.4  124.95
#Mann= 4 ,-1 , 0
  3886.9     .14       0  4576.9     .07       0  4984.1    .055       0
  5024.1     .09       0
Bank Sta=4964.1,5044.1
XS Rating Curve= 0
Exp/Cntr=.3,.1

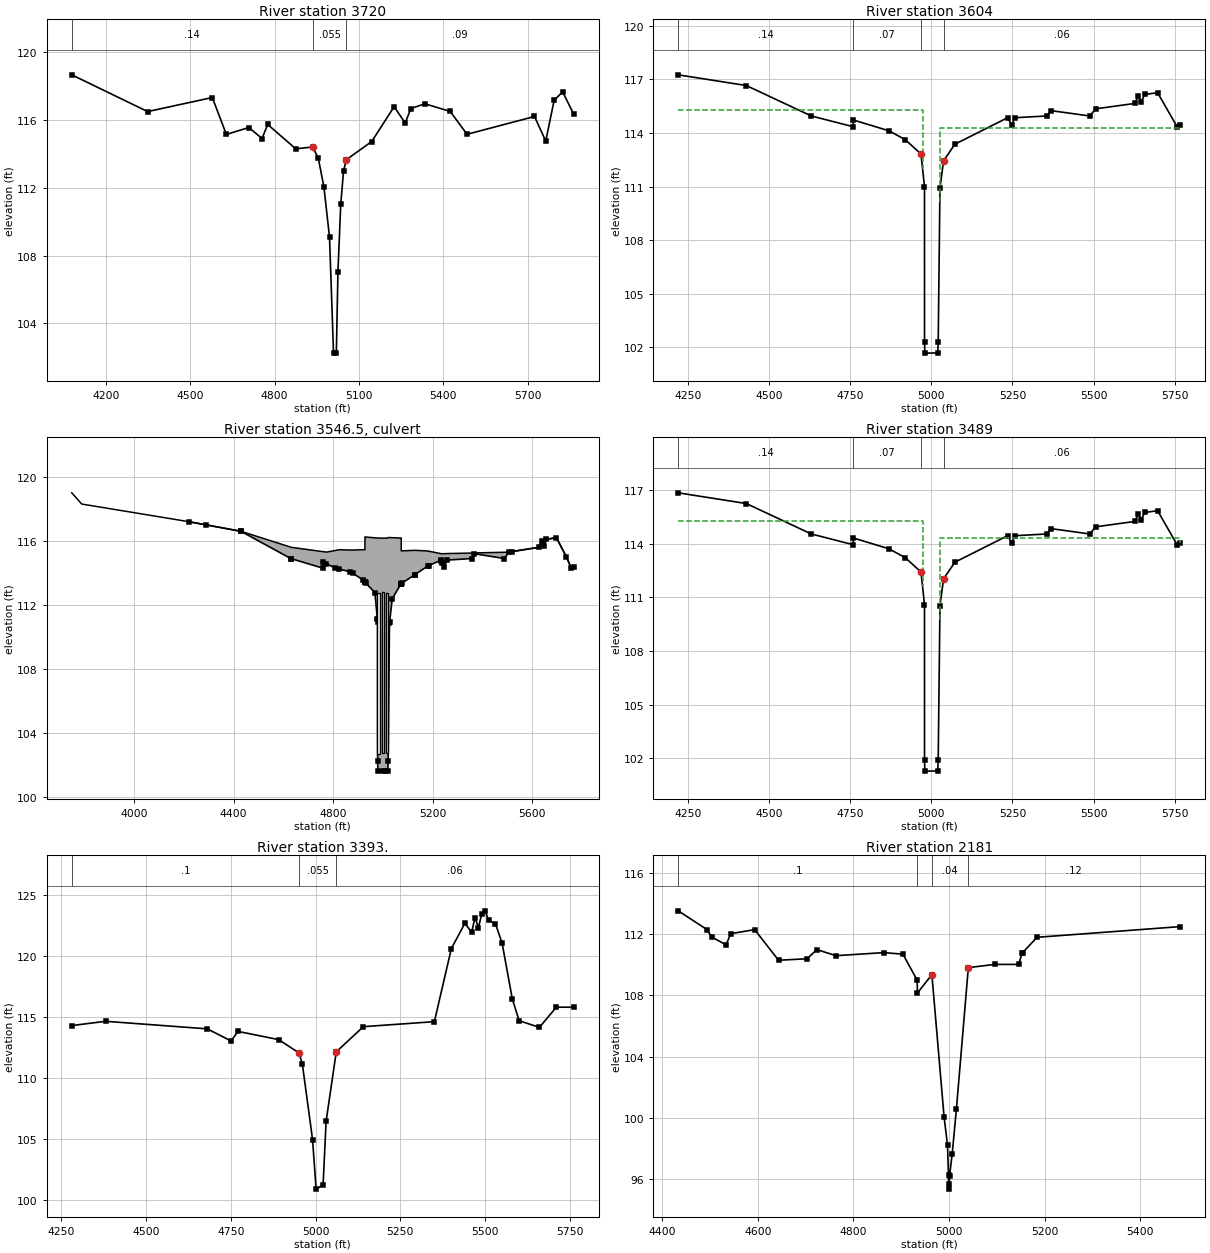
Type RM Length L Ch R = 1 ,3720    ,116,116,116
BEGIN DESCRIPTION:
E. LOUETTA - XS 4
Interpolated XS
XS 120 ft upstream of E LOUETTA
END DESCRIPTION:
XS GIS Cut Line= 4
      3097863.69      13954334.4      3097847.28     13953657.74
      3097471.26     13953360.52      3096947.11       13953011.
#Sta/Elev= 30
  4078.5  118.67  4348.5   116.5  4578.5  117.33  4628.5  115.15  4708.5  115.56
  4755.5  114.91  4775.5  115.74  4875.5   114.3  4935.5  114.41  4955.5  113.75
  4975.5  112.06  4995.5  109.09  5009.8  102.25  5019.8  102.24  5025.5  107.05
  5035.5  111.03  5045.5  113.01  5055.5  113.66  5145.5  114.73  5225.5  116.79
  5264.8  115.82  5284.8  116.68  5334.8  116.96  5424.8  116.51  5484.8  115.16
  5724.8  116.21  5764.8  114.76  5794.8  117.17  5824.8  117.67  5864.8  116.33
#Mann= 3 ,-1 , 0
  4078.5     .14       0  4935.5    .055       0  5055.5     .09       0
Bank Sta=4935.5,5055.5
XS Rating Curve= 0
Exp/Cntr=.5,.3

Type RM Length L Ch R = 1 ,3604    ,115,115,115
BEGIN DESCRIPTION:
E. LOUETTA - XS 3
Upstream Section of Bridge/Culvert/Weir
END DESCRIPTION:
XS GIS Cut Line= 4
      3097925.76       13954102.       3097912.7     13953563.43
      3097536.68     13953266.22      3097096.28      13952972.5
#Sta/Elev= 30
  4219.5  117.25  4429.5  116.65  4629.5  114.95  4758.3  114.35  4759.9  114.72
  4869.1  114.12  4919.7  113.62    4968  112.82  4978.8     111  4978.9  102.33
  4979.8  101.68  5019.8  101.69  5021.1  102.33  5026.5  110.91  5037.6  112.44
  5072.7  113.37    5235  114.85  5247.6  114.45  5257.6  114.85  5357.6  114.95
  5367.6  115.25  5487.6  114.95  5507.6  115.35  5627.6  115.65  5637.6  116.05
  5647.6  115.75  5657.6  116.15  5697.6  116.25  5757.6  114.35  5767.6  114.45
#Mann= 4 ,-1 , 0
  4219.5     .14       0  4758.3     .07       0    4968    .055       0
  5037.6     .06       0
#XS Ineff= 2 , 0
       0    4973   115.3    5026       0   114.3
Permanent Ineff=
       F       F
Bank Sta=4968,5037.6
XS Rating Curve= 0
Exp/Cntr=.5,.3

Type RM Length L Ch R = 2 ,3546.5  ,,,
BEGIN DESCRIPTION:
E. LOUETTA COMMENT: SEE PIX-US seems to have metal plates covering face of inlet-increased n-value VRR
Structure ID: K120-03-00-S1
END DESCRIPTION:
Bridge Culvert--1,0,-1,-1, 0
Deck Dist Width WeirC Skew NumUp NumDn MinLoCord MaxHiCord MaxSubmerge Is_Ogee
10,92,3,0, 59, 59, , , .95, 0, 0,0,,
  3749.5  3789.5  4219.5  4289.5    4429  4429.5  4629.5  4631.4  4758.3  4759.9
  4773.2  4808.4  4825.1  4869.1  4878.6  4919.7 4927.89    4928 4928.11  4932.1
    4968  4977.7  4978.8  4978.9  4979.8    5002  5009.8  5019.8  5021.1  5026.5
    5027  5037.6  5072.7 5073.69  5073.8 5073.91  5077.1  5127.5    5129  5181.1
  5183.5    5235  5235.6  5237.6  5247.6  5257.6  5357.6  5367.6  5487.6  5507.6
  5519.2  5627.6  5637.6  5647.6  5657.6  5697.6  5737.6  5757.6  5767.6
     119   118.3   117.2     117   116.6   116.6  115.61   115.6  115.33  115.33
   115.3   115.4  115.45  115.43  115.43  115.45  115.45  116.25  116.25  116.24
  116.19  116.18  116.18  116.18  116.18  116.17  116.17  116.19   116.2  116.21
  116.21   116.2  116.18  116.18  116.18  115.38  115.38  115.41  115.41  115.37
  115.36   115.2   115.2   115.2   115.2  115.21  115.24  115.25  115.29   115.3
  115.34   115.6     116   115.7   116.1   116.2     115   114.3   114.4
     119   118.3   117.2     117   116.6   116.6   114.9  114.89   114.3  114.67
  114.57  114.31  114.24  114.07  113.98  113.57  113.43  113.43  113.43  113.36
  112.77  111.14  110.95  102.28  101.63  101.65  101.65  101.64  102.28  110.86
  110.93  112.39  113.32  113.33  113.33  113.33  113.37  113.88   113.9  114.44
  114.46   114.8  114.75   114.6   114.4   114.8   114.9   115.2   114.9   115.3
  115.33   115.6     116   115.7   116.1   116.2     115   114.3   114.4
  3749.5  3789.5  4219.5  4289.5    4429  4429.5  4629.5  4631.4  4758.3  4759.9
  4773.2  4808.4  4825.1  4869.1  4878.6  4919.7 4927.89    4928 4928.11  4932.1
    4968  4977.7  4978.8  4978.9  4979.8    5002  5009.8  5019.8  5021.1  5026.5
    5027  5037.6  5072.7 5073.69  5073.8 5073.91  5077.1  5127.5    5129  5181.1
  5183.5    5235  5235.6  5237.6  5247.6  5257.6  5357.6  5367.6  5487.6  5507.6
  5519.2  5627.6  5637.6  5647.6  5657.6  5697.6  5737.6  5757.6  5767.6
     119   118.3   117.2     117   116.6   116.6  115.61   115.6  115.33  115.33
   115.3   115.4  115.45  115.43  115.43  115.45  115.45  116.25  116.25  116.24
  116.19  116.18  116.18  116.18  116.18  116.17  116.17  116.19   116.2  116.21
  116.21   116.2  116.18  116.18  116.18  115.38  115.38  115.41  115.41  115.37
  115.36   115.2   115.2   115.2   115.2  115.21  115.24  115.25  115.29   115.3
  115.34   115.6     116   115.7   116.1   116.2     115   114.3   114.4
   118.7     118   116.9   116.7   116.3   116.3   114.6  114.59     114  114.37
  114.27  114.01  113.94  113.77  113.68  113.27  113.13  113.13  113.13  113.06
  112.47  110.84  110.65  101.98  101.33  101.35  101.35  101.34  101.98  110.56
  110.63  112.09  113.02  113.03  113.03  113.03  113.07  113.58   113.6  114.14
  114.16   114.5  114.45   114.3   114.1   114.5   114.6   114.9   114.6     115
  115.03   115.3   115.7   115.4   115.8   115.9   114.7     114   114.1
BR Coef= 1 , 1 , 0 ,1.25, 0 ,,,.8,-1,2,0,
WSPro=,,,, 1 ,,,, 0 ,,,, 0 ,,,,-1 ,-1 ,-1 , 0 , 0 , 0 , 0 , 0
Culvert=2,10,10,92,.03,.2,1,8,3,102.72,4983,101.75,4983,Culvert #1  , 0 ,10
Culvert Bottom n=.03
Culvert=2,10,10,92,.03,.2,1,8,3,102.78,4999.7,101.77,4999.7,Culvert #2  , 0 ,10
Culvert Bottom n=.03
Culvert=2,10,10,92,.03,.2,1,8,3,102.74,5016,101.78,5016,Culvert #3  , 0 ,10
Culvert Bottom n=.03
BR U #Sta/Elev= 57
  4219.5   117.2  4289.5     117    4429   116.6  4429.5   116.6  4629.5   114.9
  4631.4  114.89  4758.3   114.3  4759.9  114.67  4773.2  114.57  4808.4  114.31
  4825.1  114.24  4869.1  114.07  4878.6  113.98  4919.7  113.57 4927.89  113.43
    4928  113.43 4928.11  113.43  4932.1  113.36    4968  112.77  4977.7  111.14
  4978.8  110.95  4978.9  102.28  4979.8  101.63    5002  101.65  5009.8  101.65
  5019.8  101.64  5021.1  102.28  5026.5  110.86    5027  110.93  5037.6  112.39
  5072.7  113.32 5073.69  113.33  5073.8  113.33 5073.91  113.33  5077.1  113.37
  5127.5  113.88    5129   113.9  5181.1  114.44  5183.5  114.46    5235   114.8
  5235.6  114.75  5237.6   114.6  5247.6   114.4  5257.6   114.8  5357.6   114.9
  5367.6   115.2  5487.6   114.9  5507.6   115.3  5519.2  115.33  5627.6   115.6
  5637.6     116  5647.6   115.7  5657.6   116.1  5697.6   116.2  5737.6     115
  5757.6   114.3  5767.6   114.4
BR U #Mann= 6
  4219.5     .99  4631.4     .14  4758.3     .07    4968    .055  5037.6     .06
  5519.2     .99
BR U Banks=4968,5037.6
BR D #Sta/Elev= 57
  4219.5   116.9  4289.5   116.7    4429   116.3  4429.5   116.3  4629.5   114.6
  4631.4  114.59  4758.3     114  4759.9  114.37  4773.2  114.27  4808.4  114.01
  4825.1  113.94  4869.1  113.77  4878.6  113.68  4919.7  113.27 4927.89  113.13
    4928  113.13 4928.11  113.13  4932.1  113.06    4968  112.47  4977.7  110.84
  4978.8  110.65  4978.9  101.98  4979.8  101.33    5002  101.35  5009.8  101.35
  5019.8  101.34  5021.1  101.98  5026.5  110.56    5027  110.63  5037.6  112.09
  5072.7  113.02 5073.69  113.03  5073.8  113.03 5073.91  113.03  5077.1  113.07
  5127.5  113.58    5129   113.6  5181.1  114.14  5183.5  114.16    5235   114.5
  5235.6  114.45  5237.6   114.3  5247.6   114.1  5257.6   114.5  5357.6   114.6
  5367.6   114.9  5487.6   114.6  5507.6     115  5519.2  115.03  5627.6   115.3
  5637.6   115.7  5647.6   115.4  5657.6   115.8  5697.6   115.9  5737.6   114.7
  5757.6     114  5767.6   114.1
BR D #Mann= 6
  4219.5     .99  4631.4     .14  4758.3     .07    4968    .055  5037.6     .06
  5519.2     .99
BR D Banks=4968,5037.6
BC Design=,, 0 ,, 0 ,,,,,,
BC HTab HWMax=117.25

Type RM Length L Ch R = 1 ,3489    ,96,96,84
BEGIN DESCRIPTION:
E. LOUETTA - XS 2
Downstream Section of Bridge/Culvert/Weir
END DESCRIPTION:
XS GIS Cut Line= 4
       3098006.4      13954021.9      3097993.32     13953482.57
       3097609.3     13953179.03      3097175.33      13952889.6
#Sta/Elev= 30
  4219.5  116.85  4429.5  116.25  4629.5  114.55  4758.3  113.95  4759.9  114.32
  4869.1  113.72  4919.7  113.22    4968  112.42  4978.8   110.6  4978.9  101.93
  4979.8  101.28  5019.8  101.29  5021.1  101.93  5026.5  110.51  5037.6  112.04
  5072.7  112.97    5235  114.45  5247.6  114.05  5257.6  114.45  5357.6  114.55
  5367.6  114.85  5487.6  114.55  5507.6  114.95  5627.6  115.25  5637.6  115.65
  5647.6  115.35  5657.6  115.75  5697.6  115.85  5757.6  113.95  5767.6  114.05
#Mann= 4 ,-1 , 0
  4219.5     .14       0  4758.3     .07       0    4968    .055       0
  5037.6     .06       0
#XS Ineff= 2 , 0
       0    4973   115.3    5026       0   114.3
Permanent Ineff=
       F       F
Bank Sta=4968,5037.6
XS Rating Curve= 0
Exp/Cntr=.5,.3

Type RM Length L Ch R = 1 ,3393.   ,1212,1212,1218
BEGIN DESCRIPTION:
E. LOUETTA - XS 1
Interpolated channel - LIDAR overbanks
END DESCRIPTION:
XS GIS Cut Line= 4
      3098443.62      13953708.5      3098067.88     13953425.22
      3097683.85     13953121.68      3097249.89     13952832.31
#Sta/Elev= 30
  4280.7  114.31  4380.7  114.66  4680.7  114.04  4750.7  113.05  4771.3  113.83
  4891.3  113.16  4951.3  112.07  4961.3  111.13  4991.3  104.97 5001.76  100.91
 5022.39  101.25  5031.3  106.47  5061.3  112.16  5141.3  114.22  5350.8  114.63
  5400.8  120.61  5440.8  122.69  5460.8  121.96  5470.8  123.16  5480.8  122.34
  5490.8  123.47  5500.8  123.71  5510.8  122.92  5530.8  122.67  5550.8  121.05
  5580.8  116.49  5600.8  114.71  5660.8  114.16  5710.8  115.82  5762.4  115.81
#Mann= 3 ,-1 , 0
  4280.7      .1       0  4951.3    .055       0  5061.3     .06       0
Bank Sta=4951.3,5061.3
XS Rating Curve= 0
Exp/Cntr=.3,.1

Type RM Length L Ch R = 1 ,2181    ,1459.9,1488,1499.9
BEGIN DESCRIPTION:
Cross Section K120-03-00-X2
END DESCRIPTION:
XS GIS Cut Line= 4
      3098564.71      13952774.6      3098581.14     13952349.22
      3098347.89     13952175.77      3098039.03      13952045.9
#Sta/Elev= 30
  4433.2  113.53  4493.2  112.31  4503.2  111.82  4533.2  111.31  4543.2  112.04
  4593.2   112.3  4643.2   110.3  4703.2   110.4  4723.2     111  4763.2   110.6
  4863.4   110.8  4903.4   110.7  4933.4     109  4933.8  108.16  4964.1  109.36
  4989.7  100.05  4996.8   98.23  4998.9   96.25  4999.3   95.68  5000.7   95.35
    5001   96.19  5006.6   97.65  5015.5   100.6  5040.4  109.82  5095.9  110.03
  5145.6  110.03  5153.4   110.8  5154.1   110.8  5184.1   111.8  5484.1   112.5
#Mann= 4 ,-1 , 0
  4433.2      .1       0  4933.4    .045       0  4964.1     .04       0
  5040.4     .12       0
Bank Sta=4964.1,5040.4
XS Rating Curve= 0
Exp/Cntr=.3,.1

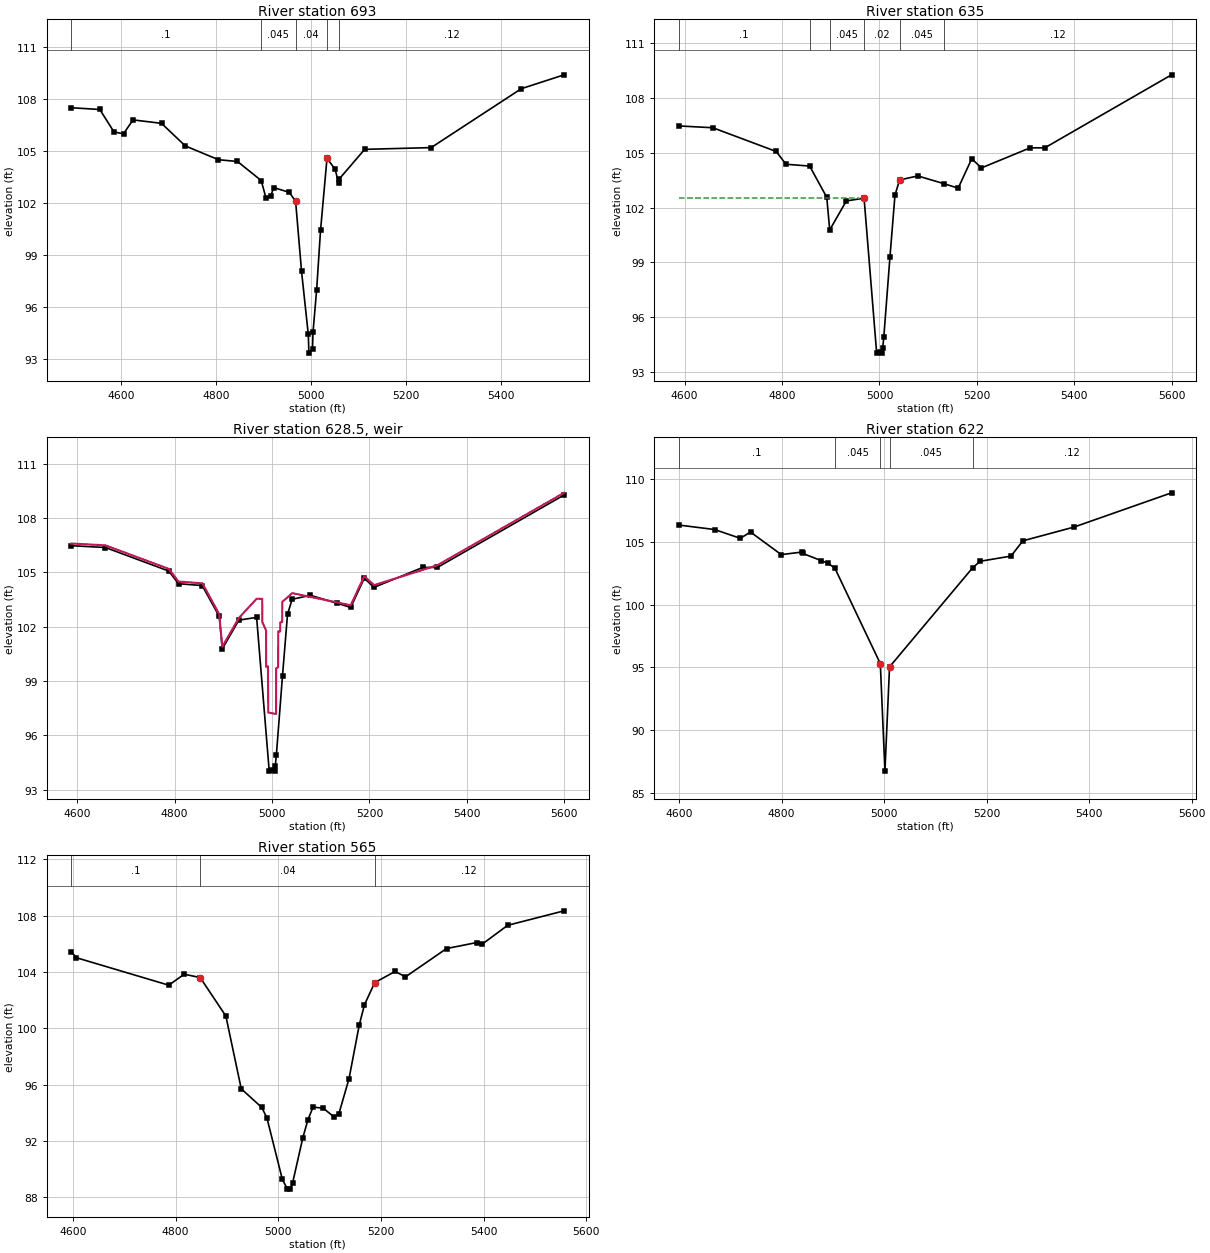
Type RM Length L Ch R = 1 ,693     ,59,58,58
BEGIN DESCRIPTION:
Weir - XS 4
Cross Section K120-03-00-X01
END DESCRIPTION:
XS GIS Cut Line= 4
      3099435.24      13951819.6      3099589.87     13951423.01
      3099520.14     13951242.75      3099115.35      13951135.9
#Sta/Elev= 30
  4495.8   107.5  4555.8   107.4  4585.8   106.1  4605.8     106  4625.8   106.8
  4685.8   106.6  4735.8   105.3  4805.8   104.5  4845.8   104.4  4895.8   103.3
  4905.8   102.3  4915.8   102.4  4922.2  102.89    4955  102.62  4968.3   102.1
  4980.8   98.06    4995   94.42  4996.3   93.34  5003.9   93.59    5005   94.56
  5012.6      97  5020.8  100.42  5034.4  104.58  5051.5  103.95  5058.8  103.17
  5060.5   103.4  5113.8   105.1  5253.8   105.2  5443.8   108.6  5533.8   109.4
#Mann= 5 ,-1 , 0
  4495.8      .1       0  4895.8    .045       0  4968.3     .04       0
  5034.4    .045       0  5060.5     .12       0
Bank Sta=4968.3,5034.4
XS Rating Curve= 0
Exp/Cntr=.7,.5

Type RM Length L Ch R = 1 ,635     ,13,13,13
BEGIN DESCRIPTION:
Weir - XS 3
Upstream Section of Bridge/Culvert/Weir
END DESCRIPTION:
XS GIS Cut Line= 4
      3099538.58      13951737.7       3099655.3      13951486.3
      3099570.96      13951196.1      3099149.75      13951085.1
#Sta/Elev= 25
  4588.1  106.48  4658.1  106.38  4788.1  105.08  4808.1  104.38  4856.7  104.28
  4891.8  102.57  4897.9  100.78    4932  102.37  4968.4  102.52  4994.2   94.04
  5000.1   94.11  5005.9   94.03  5006.7   94.33  5008.9   94.92  5021.5    99.3
  5031.8  102.69  5041.3  103.52  5078.7  103.74  5132.9  103.31  5161.5  103.07
  5189.3  104.68  5209.3  104.18  5309.3  105.28  5339.3  105.28  5599.3  109.28
#Mann= 6 ,-1 , 0
  4588.1      .1       0  4856.7     .99       0  4897.9    .045       0
  4968.4     .02       0  5041.3    .045       0  5132.9     .12       0
#XS Ineff= 2 , 0
       0  4958.4  102.53  5051.3       0  103.51
Permanent Ineff=
       F       F
Bank Sta=4968.4,5041.3
XS Rating Curve= 0
Exp/Cntr=.7,.5

Type RM Length L Ch R = 5 ,628.5   ,,,
BEGIN DESCRIPTION:
WEIR 430' US K120-00-00
Structure ID: K120-03-00-S1-1
END DESCRIPTION:
IW Pilot Flow=0
#Inline Weir SE= 30
  4588.1   106.6  4658.1   106.5  4788.1   105.2  4808.1   104.5  4857.2   104.4
  4891.8  102.69  4897.9   100.9    4932  102.49  4968.4  103.55  4979.9  103.54
  4980.1  102.26  4987.8   101.8  4987.9   99.79  4991.7   99.82  4992.2   97.27
  5006.7   97.19  5008.3   97.19  5008.4    99.7  5012.5   99.77  5012.7  101.75
  5016.7  101.74 5016.81  102.24  5020.8  102.26  5021.1  103.38  5041.5  103.86
  5161.5  103.19  5189.3   104.8  5209.3   104.3  5339.3   105.4  5599.3   109.4
IW Dist,WD,Coef,Skew,MaxSub,Min_El,Is_Ogee,SpillHt,DesHd
5,1,3,0,.95,, 0 ,,,0,0,

Type RM Length L Ch R = 1 ,622     ,56,57,57
BEGIN DESCRIPTION:
Weir - XS 2
Cross Section FIELD_DS
Located At: WEIR 430' US K120-00-00
END DESCRIPTION:
XS GIS Cut Line= 6
      3099577.14      13951726.5        3099605.      13951662.3
      3099673.15      13951505.2      3099576.76      13951168.8
      3099403.68      13951122.6      3099220.12      13951073.5
#Sta/Elev= 19
  4599.2  106.36  4669.2     106  4719.2   105.3  4739.2   105.8  4799.2     104
  4839.2   104.2  4840.8   104.1  4877.7  103.51  4890.8   103.3  4903.8  102.92
  4992.5    95.3  5001.5   86.72  5010.5   95.04  5173.1  102.97  5187.6  103.47
  5247.4  103.88  5270.7   105.1  5370.7   106.2  5560.7  108.93
#Mann= 5 ,-1 , 0
  4599.2      .1       0  4903.8    .045       0  4992.5     .04       0
  5010.5    .045       0  5173.1     .12       0
Bank Sta=4992.5,5010.5
XS Rating Curve= 0
Exp/Cntr=.7,.5

Type RM Length L Ch R = 1 ,565     ,0,0,0
BEGIN DESCRIPTION:
Weir - XS 1
Extrapolated channel - LIDAR overbanks
END DESCRIPTION:
XS GIS Cut Line= 6
      3099631.86      13951710.5      3099659.72     13951646.29
      3099727.86      13951489.2      3099631.47     13951152.79
      3099458.39     13951106.59      3099274.84     13951057.53
#Sta/Elev= 30
  4596.6  105.45  4606.6  105.02  4786.6  103.07  4816.6  103.85  4847.8  103.61
  4897.8  100.88  4927.8   95.71  4967.8   94.39  4977.8   93.65  5007.8   89.29
  5017.8   88.59  5023.5    88.6  5027.8   89.02  5047.8   92.24  5057.8   93.52
  5067.8   94.42  5087.8   94.33  5107.8   93.74  5117.8   93.91  5137.8   96.43
  5157.8  100.25  5167.8  101.67  5187.8  103.25  5227.8  104.05  5247.8  103.66
  5327.8  105.67  5386.9   106.1  5396.9  105.97  5446.9  107.32  5556.9  108.35
#Mann= 3 ,-1 , 0
  4596.6      .1       0  4847.8     .04       0  5187.8     .12       0
Bank Sta=4847.8,5187.8
XS Rating Curve= 0
Exp/Cntr=.3,.1

Chan Stop Cuts=-1